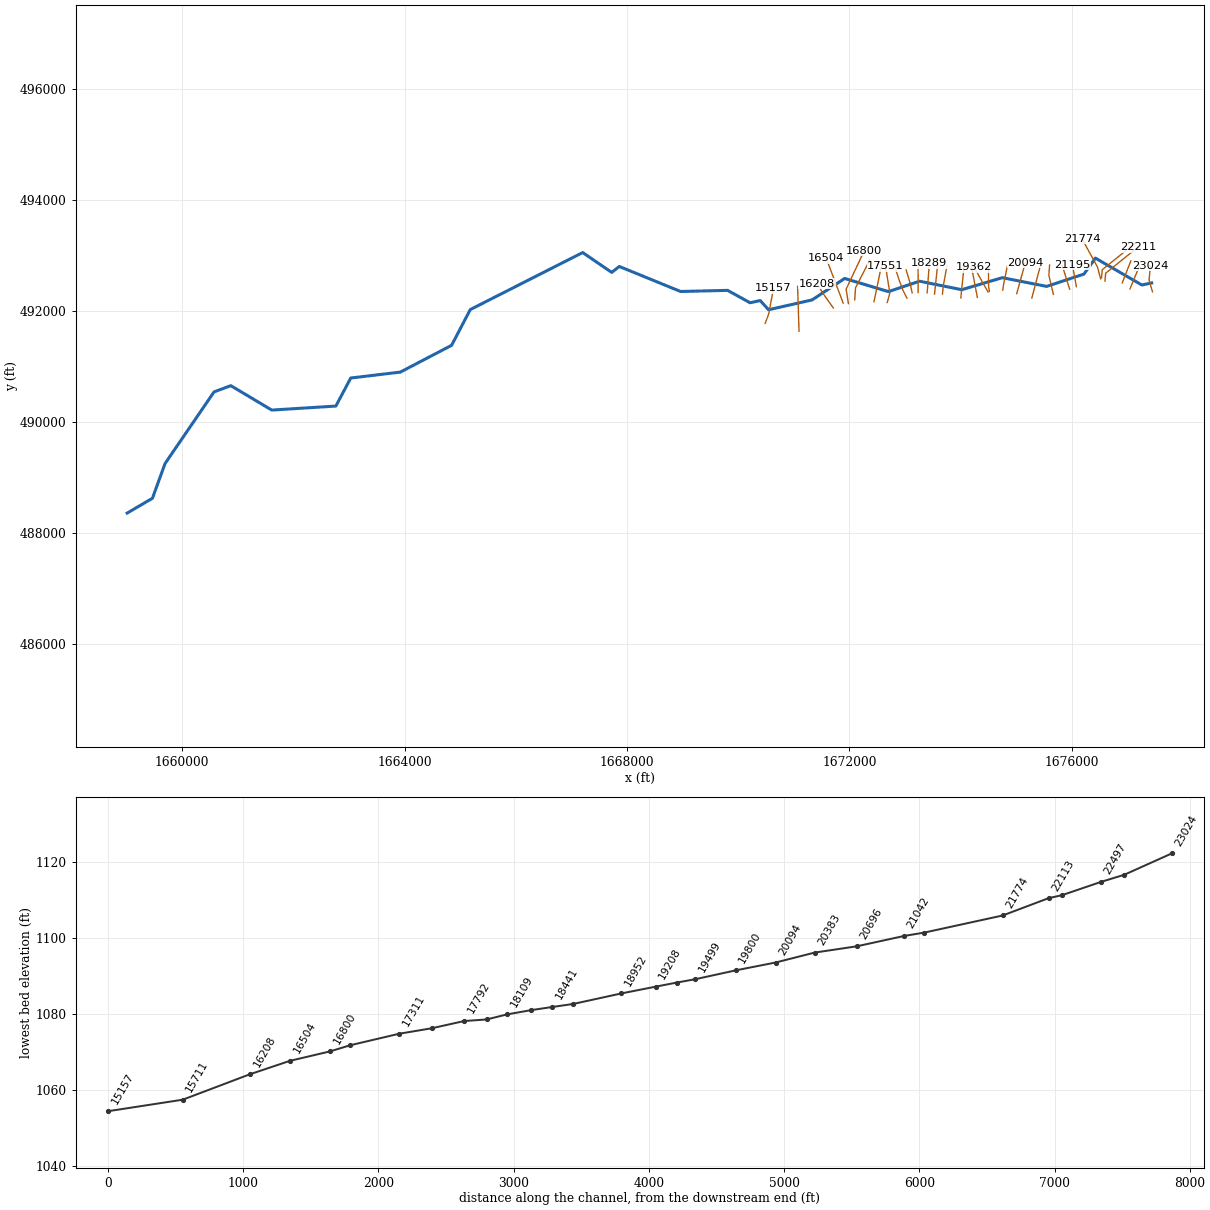
--- NFGraveCk.prj (project) ---

Proj Title=NFGraveCk
Current Plan=p01
Default Exp/Contr=0,0
English Units
Geom File=g01
Flow File=f01
Plan File=p01
BEGIN DESCRIPTION:
---------- MODELED AS PART OF WVEM CTP PROGRAM, 2025----------
Stream Name: North Fork Grave Creek
Flood Zone: AFH
Marshall County, WV
HEC-RAS Version: RAS 6.6
Vertical Datum: NAVD88
Projection: NAD 1983 StatePlane West Virginia N FIPS 4701 (US Feet)
Terrain: 1-meter West Virginia FEMA R3 South Central (collected 2018-2019)
Land Use: 2024 NLCD
Hydrologic Method:
Duda et al., "Estimation of magnitude and frequency of floods for rural, unregulated streams in and near Virginia and West Virginia." September 8, 2025.
Additional Model Notes:
Coincident peak with Grave Creek modeled as normal depth
END DESCRIPTION:
DSS Export Rating Curves= 0
DSS Export Rating Curve Sorted= 0
DSS Export Volume Flow Curves= 0
DXF OffsetX= 0
DXF OffsetY= 0
DXF ScaleX= 0
DXF ScaleY= 0

--- NFGraveCk.p01 (plan) ---

Plan Title=Floodplain
Program Version=6.60
Short Identifier=Floodplain
Geom File=g01
Flow File=f01
Subcritical Flow
K Sum by GR= 0
Std Step Tol= 0.01
Critical Tol= 0.01
Num of Std Step Trials= 20
Max Error Tol= 0.3
Flow Tol Ratio= 0.001
Split Flow NTrial= 30
Split Flow Tol= 0.02
Split Flow Ratio= 0.02
Log Output Level= 0
Friction Slope Method= 1
Unsteady Friction Slope Method= 2
Unsteady Bridges Friction Slope Method= 1
Parabolic Critical Depth
Global Vel Dist= 0 , 0 , 0
Global Log Level= 0
CheckData=False
Encroach Param=-1 ,0,0, 0
Flow Ratio Tolerance=0.1
Flow Ratio Min Ratio=0.5
Flow Ratio Max Ratio=4
Flow Ratio Max Iterations= 10
Mapping Interval=1HOUR
Computation Time Step Use Courant=        0
Computation Time Step Use Time Series=    0
Computation Time Step Count To Double=0
Computation Time Step Max Doubling=0
Computation Time Step Max Halving=0
Computation Time Step Residence Courant=0
Run HTab= 0
Run UNet= 0
Run Sediment= 0
Run PostProcess= 0
Run WQNet= 0
Run RASMapper=-1
UNET Theta= 0
UNET Theta Warmup= 0
UNET ZTol= 0
UNET ZSATol= 0
UNET MxIter= 0
UNET Max Iter WO Improvement= 0
UNET MaxInSteps= 0
UNET DtIC= 0
UNET DtMin= 0
UNET MaxCRTS= 0
UNET WFStab= 0
UNET SFStab= 0
UNET WFX= 1
UNET SFX= 1
UNET Gravity=32.17405
UNET 1D Methodology=Finite Difference
UNET DSS MLevel= 1
UNET Pardiso=0
UNET DZMax Abort= 0
UNET Use Existing IB Tables= 0
UNET Froude Reduction=False
UNET Froude Limit= 0
UNET Froude Power= 0
UNET D1 Cores= 0
UNET WindReference=Eulerian
UNET WindDragFormulation=Hsu (1988)
UNET D2 Coriolis=0
UNET D2 Cores= 0
UNET D2 Theta= 1
UNET D2 Theta Warmup= 1
UNET D2 Z Tol= 0.01
UNET D2 Volume Tol= 0.01
UNET D2 Max Iterations= 20
UNET D2 Advanced Convergence=0
UNET D2 WS Max Tol=0.15
UNET D2 WS RMS Tol=0.002
UNET D2 WS Stall Tol=1
UNET D2 Equation= 0
UNET D2 RampUpFraction=0.1
UNET D2 TimeSlices= 1
UNET D2 Turbulence Formulation=Non-Conservative (original)
UNET D2 Eddy Viscosity=0.3
UNET D2 Transverse Eddy Viscosity=0.1
UNET D2 Smagorinsky Mixing=0
UNET D2 BCVolumeCheck=0
UNET D2 Cores=0
UNET D2 SolverType=PARDISO (Direct)
UNET D2 Minimum Iterations= 3
UNET D2 Maximum Iterations= 30
UNET D2 Restart Number= 10
UNET D2 Relaxation Coeff=1.3
UNET D2 SOR Precondition Iterations= 10
UNET D2 ILUT Maximum Fill= 8
UNET D2 ILUT Tolerance=1E-08
UNET D2 Convergence Tolerance=0.00001
PS Theta= 1
PS WS Tol= 0.01
PS Volume Tol= 0.01
PS Max Iterations= 20
PS Equation= 0
PS Advance Time Step=-1
PS Target Courant=0.9
PS Time Slices= 1
PS Iterate With 2D=0
PS Project Initial WSE from DS=-1
PS Ramp Up Initial WSE from US=-1
PS Cores=0
UNET D1D2 MaxIter= 0
UNET D1D2 ZTol=0.01
UNET D1D2 QTol=0.1
UNET D1D2 MinQTol=1
Write IC File= 0
Write IC File at Fixed DateTime=0
Write IC File at Sim End=0
Echo Input=False
Echo Parameters=False
Echo Output=False
Write Detailed= 0
HDF Write Warmup=0
HDF Write Time Slices=0
HDF Flush=0
HDF Compression= 1
HDF Chunk Size= 1
HDF Spatial Parts= 1
HDF Use Max Rows=0
HDF Fixed Rows= 1
Calibration Method= 0
Calibration Iterations= 20
Calibration Max Change=0.05
Calibration Tolerance=0.2
Calibration Maximum=1.5
Calibration Minimum=0.5
Calibration Optimization Method= 1
WQ AD Non Conservative
WQ ULTIMATE=-1
WQ Max Comp Step=1HOUR
WQ Output Interval=15MIN
WQ Output Selected Increments= 0
WQ Create Restart=0
WQ Fixed Restart=0
WQ System Summary=0
WQ Write To DSS=0
Sorting and Armoring Iterations= 10
XS Update Threshold= 0.02
Bed Roughness Predictor= 0
Processes Affected by Predictor=Sediment Only
Hydraulics Update Threshold= 0.02
Energy Slope Method= 1
Volume Change Method= 1
Sediment Retention Method= 0
Sediment TS Multiplier= 1
Warm Up Method= 0
XS Weighting Method= 0
Number of US Weighted Cross Sections= 1
Number of DS Weighted Cross Sections= 1
Upstream XS Weight=0
Main XS Weight=1
Downstream XS Weight=0
Number of DS XS's Weighted with US Boundary= 1
Upstream Boundary Weight= 1
Weight of XSs Associated with US Boundary= 0
Number of US XS's Weighted with DS Boundary= 1
Downstream Boundary Weight= 0.5
Weight of XSs Associated with DS Boundary= 0.5
Percentile Method= 0
Sediment Output Level= 3
Mass or Volume Output= 0
Output Increment Type= 1
Profile and TS Output Increment= 1
Transport Output Increment 1
XS Output Flag= 0
XS Output Increment= 10
Read HDF5 Sediment Hotstart= 0
Sediment Hotstart Type= 0
Write Gradation File= 0
Read Gradation Hotstart= 0
Write HDF5 File= 1
Write Binary Output= 1
Write DSS Sediment File= 0
DSS Sediment Output Type= 1
SV Curve= 0
Specific Gage Flag= 0
Subcell Erosion Methods= 0
Subcell Deposition Methods= 0
Advection Scheme= 1
Matrix Solver= 0
Implicit Weighting Factor= 1
Maximum Outer Loop Convergence Iterations= 5
Convergence Maximum Absolute= 0.001
Convergence RMSE= 0.0001
Grain Fractions Max Abs Error= 0.001
Max Subgrid Regions= 1
Max Subgrid Length Scale= 3.402823E+38
Initial Layer Thickness= 3
Min Layer Thickness= 0.1
Max Layer Thickness= 6
Number of Layers= 5

--- NFGraveCk.f01 (steady flow) ---

Flow Title=Flow
Program Version=6.60
Number of Profiles= 1
Profile Names=P100yr
River Rch & RM=NFGraveCk,Main,23024
     997
River Rch & RM=NFGraveCk,Main,19499
    1120
River Rch & RM=NFGraveCk,Main,16948
    1650
River Rch & RM=NFGraveCk,Main,11742
    1880
River Rch & RM=NFGraveCk,Main,9901
    2300
Boundary for River Rch & Prof#=NFGraveCk,Main            , 1
Up Type= 0
Dn Type= 3
Dn Slope=0.00197
DSS Import GetInterval= 0
DSS Import GetPeak= 0
DSS Import FillOption= 0

--- NFGraveCk.g01 (geometry) ---

Geom Title=Geometry
Program Version=6.60

River Reach=NFGraveCk       ,Main
Reach XY= 30
1677435.16552445492510.951213761     1677258.013      492473.797
      1676422.69      492958.231     1676216.614      492670.144
     1675546.196      492448.348     1674748.904      492605.541
     1674019.097      492388.944     1673260.331      492542.134
     1672702.177      492354.446     1671913.399      492591.424
     1671327.863      492204.708     1670545.308      492027.784
     1670394.825      492193.254     1670212.511      492153.738
      1669809.42      492376.845     1668963.424      492356.799
      1667861.33      492807.681     1667725.078      492700.787
     1667202.651      493058.356     1665181.521      492031.024
     1664845.587      491386.842     1663924.389      490904.513
     1663031.445      490797.211     1662764.355      490292.059
     1661611.025      490219.852     1660875.278      490659.893
     1660573.258      490547.104     1659693.304      489257.383
      1659466.22       488631.25     1659011.625      488363.502

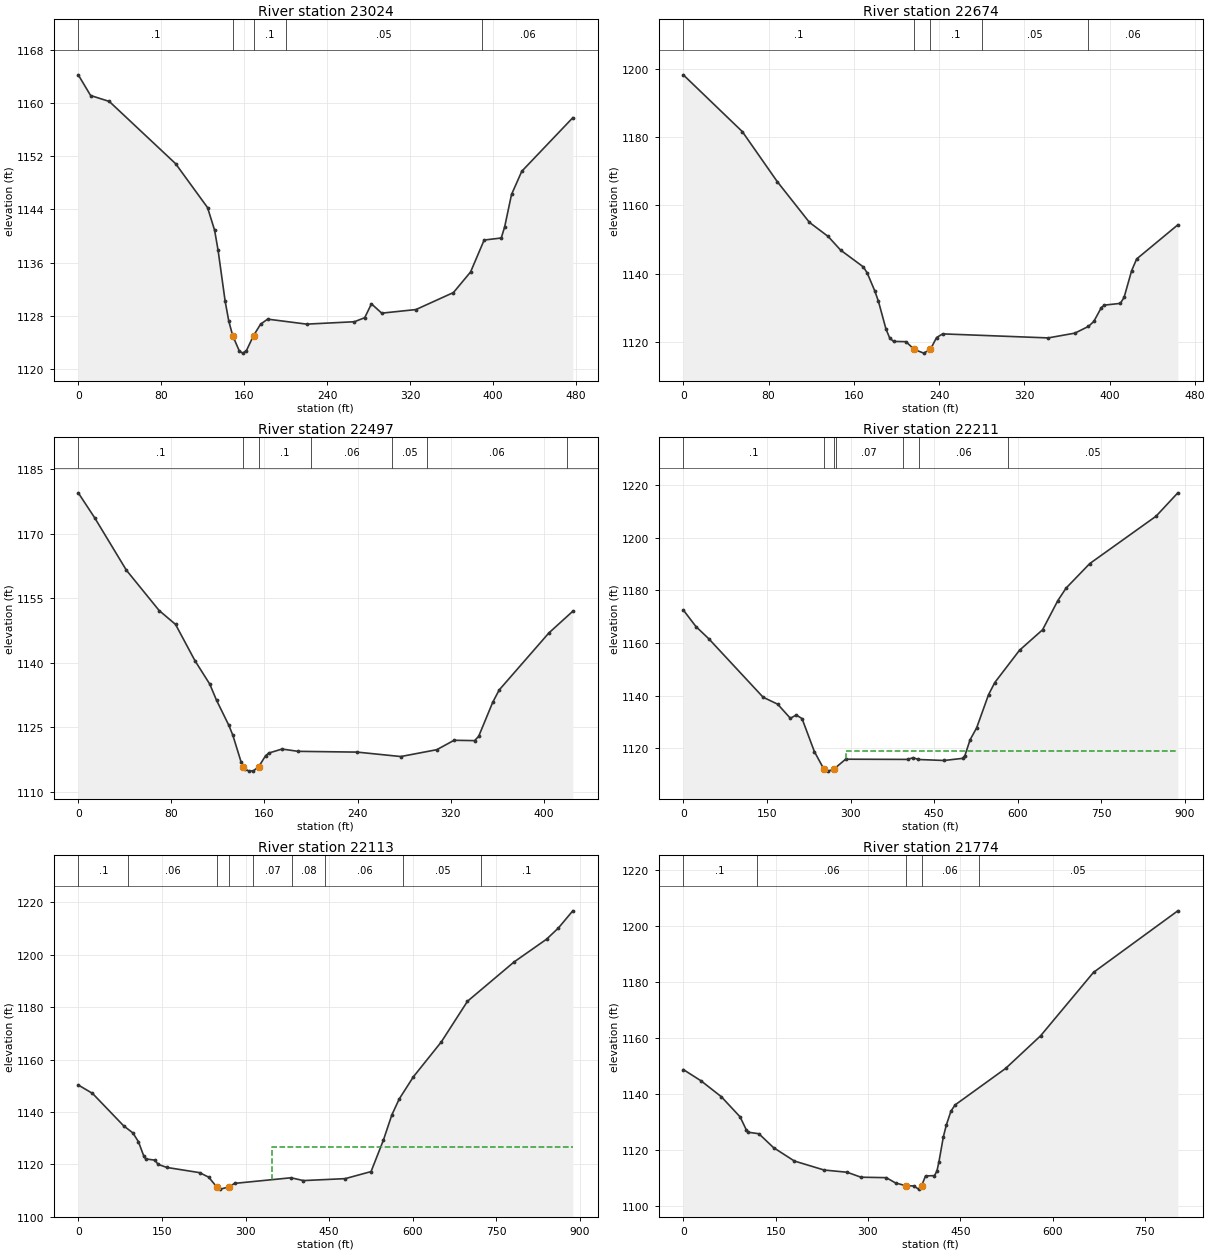
Type RM Length L Ch R = 1 ,23024   ,356.7,350.9,343.2
XS GIS Cut Line= 3
1677449.01775724492351.1493961621677388.01688101492561.774537509
1677410.62189789492818.470778013
#Sta/Elev= 30
       0 1164.23    11.9 1161.12    29.9 1160.23    93.9 1150.87   124.7 1144.27
   131.5 1140.87   134.9 1137.82   141.7 1130.17   145.2  1127.2   148.9 1125.04
   155.4 1122.69   158.8 1122.39   162.2 1122.77   169.1 1125.04   175.9 1126.75
   182.7  1127.5   220.3 1126.75   266.4 1127.11   276.3 1127.72   282.8  1129.8
   292.7  1128.4   325.7 1128.94   361.9  1131.5   378.4 1134.59   391.5 1139.39
     408  1139.7   411.3 1141.38   417.9 1146.24   427.8 1149.73     477 1157.78
#Mann= 5, -1 ,  0
       0     0.1       0   148.9   0.045       0   169.1     0.1       0
     200    0.05       0  389.28    0.06       0
Bank Sta=148.9,169.1
XS Rating Curve= 0 ,0
Exp/Cntr=0.3,0.1

Type RM Length L Ch R = 1 ,22674   ,175.1,176.1,175.7
XS GIS Cut Line= 2
1677044.78816667492403.2257930931677220.39092728492832.464688946
#Sta/Elev= 30
       0 1198.16    55.4 1181.54    88.1 1166.94   118.3 1155.01   135.9 1150.88
   147.5 1146.91   168.8    1142   172.4 1140.27   179.5 1135.04     183 1131.94
   190.1  1123.8   193.6 1121.18   197.2 1120.19   208.9 1120.12  216.481117.859
   225.5 1116.77  231.78 1117.86   237.5 1121.32   243.3  1122.4   342.2 1121.22
   367.3 1122.62     380 1124.59     385 1126.03   392.1 1130.11     395 1130.81
   409.9 1131.32   413.4 1133.07   420.5  1140.9   425.2 1144.31   463.8 1154.29
#Mann= 5, -1 ,  0
       0     0.1       0  216.48   0.045       0  231.78     0.1       0
     280    0.05       0     380    0.06       0
Bank Sta=216.48,231.78
XS Rating Curve= 0 ,0
Exp/Cntr(USF)=0,0
Exp/Cntr=0.3,0.1

Type RM Length L Ch R = 1 ,22497   ,289.7,285.9,280.2
XS GIS Cut Line= 2
1676905.57852711 492511.120173721677059.82985902492907.146940721
#Sta/Elev= 30
       0 1179.52    14.2 1173.68    41.3 1161.56    69.5 1152.17    83.6 1148.94
   100.3  1140.5     113 1135.07   118.8 1131.33   129.4 1125.49   132.9 1123.14
   139.9    1117  141.981115.902   143.4 1115.23     147 1114.84   150.5 1114.91
  155.141115.902     161 1118.42   163.7 1119.04   175.1 1119.97     189 1119.44
   239.7 1119.26   277.2 1118.23   308.1 1119.82     323 1122.01   340.6 1121.93
   344.1 1122.92   356.2 1130.84   361.7 1133.69   404.4 1146.94     425    1152
#Mann= 7, -1 ,  0
       0     0.1       0  141.98   0.045       0  155.14     0.1       0
     200    0.06       0     270    0.05       0     300    0.06       0
     420    0.05       0
Bank Sta=141.98,155.14
XS Rating Curve= 0 ,0
Exp/Cntr(USF)=0,0
Exp/Cntr=0.3,0.1

Type RM Length L Ch R = 1 ,22211   ,96.3,98.6,99.2
XS GIS Cut Line= 3
1676594.77531392492543.4950799541676607.24547457492686.175406679
1677185.48618278493154.134175855
#Sta/Elev= 30
       0 1172.57    22.6 1166.29    45.7 1161.64   143.2 1139.43   169.3 1136.79
   192.1 1131.43   202.6 1132.69     213 1131.32   235.1 1118.81  251.851112.261
   259.9 1111.37  270.79 1112.26   291.2  1115.9   402.5 1115.82   412.4 1116.48
   421.6 1115.79   467.8 1115.41     501 1116.22   505.1 1117.24   514.5  1123.3
   526.2 1127.79   547.5 1140.37   558.8 1145.02   603.1 1157.27   644.5 1165.05
   671.9 1176.14   686.7 1180.88   729.1 1190.18   848.1 1208.18   887.1 1217.05
#Mann= 7, -1 ,  0
       0     0.1       0  251.85   0.045       0  270.79    0.06       0
  273.22    0.07       0  393.22    0.08       0  423.22    0.06       0
  583.22    0.05       0
#XS Ineff= 2 , 0
                           291.7         1118.94
Permanent Ineff=
       F       F
Bank Sta=251.85,270.79
XS Rating Curve= 0 ,0
Exp/Cntr(USF)=0,0
Exp/Cntr=0.3,0.1

Type RM Length L Ch R = 1 ,22113   ,309.5,339,344.8
XS GIS Cut Line= 3
 1676533.3461067492606.2707704371676545.81626735492748.951097162
1677124.05697557493216.909866338
#Sta/Elev= 30
       0 1150.31    25.5 1147.11    81.5 1134.72    97.9 1132.04   107.8 1128.74
   117.7 1123.11     121 1122.12   137.4 1121.64   143.2 1120.03     159 1118.86
   217.5 1116.88     234 1115.15  248.021111.512   255.1 1110.59   271.21111.512
   280.3 1112.78   381.7 1114.92   403.9 1113.85   478.8 1114.59   525.2 1117.28
   547.3 1129.24   562.5  1138.9   575.8    1145   601.2 1153.45   651.2 1166.73
   698.2 1182.25   781.8 1197.24   840.1 1205.93   861.1 1210.15   887.1 1216.74
#Mann= 9, -1 ,  0
       0     0.1       0      90    0.06       0  248.02   0.045       0
   271.2    0.06       0  313.22    0.07       0  383.22    0.08       0
  443.22    0.06       0  583.22    0.05       0  723.22     0.1       0
#XS Ineff= 2 , 0
                          347.65          1126.5
Permanent Ineff=
       F       F
Bank Sta=248.02,271.2
XS Rating Curve= 0 ,0
Exp/Cntr(USF)=0,0
Exp/Cntr=0.3,0.1

Type RM Length L Ch R = 1 ,21774   ,555.6,578.6,566.1
XS GIS Cut Line= 3
1676516.51912065492585.0580785341676460.41064328492797.873160843
1676180.08380146493309.499759449
#Sta/Elev= 30
       0  1148.8    28.9 1144.75    61.8 1139.08    92.3 1131.87   102.5 1127.17
   105.9 1126.36   122.8 1125.84   146.6 1120.87   180.5 1116.08   228.8 1112.86
   266.2 1112.07   288.7 1110.29   329.8 1110.13   344.8 1108.24  362.041107.226
   374.3 1107.18   382.2 1106.03   387.11107.225   393.6 1110.74   408.1 1110.86
   412.1 1112.48   415.4 1115.84   422.6  1124.8   427.4 1128.97   434.9 1133.94
   441.7 1136.16   523.7 1149.19   580.5 1160.86   666.5 1183.55   803.5 1205.56
#Mann= 5, -1 ,  0
       0     0.1       0     120    0.06       0  362.04   0.045       0
   387.1    0.06       0  480.09    0.05       0
Bank Sta=362.04,387.1
XS Rating Curve= 0 ,0
Exp/Cntr(USF)=0,0
Exp/Cntr=0.3,0.1

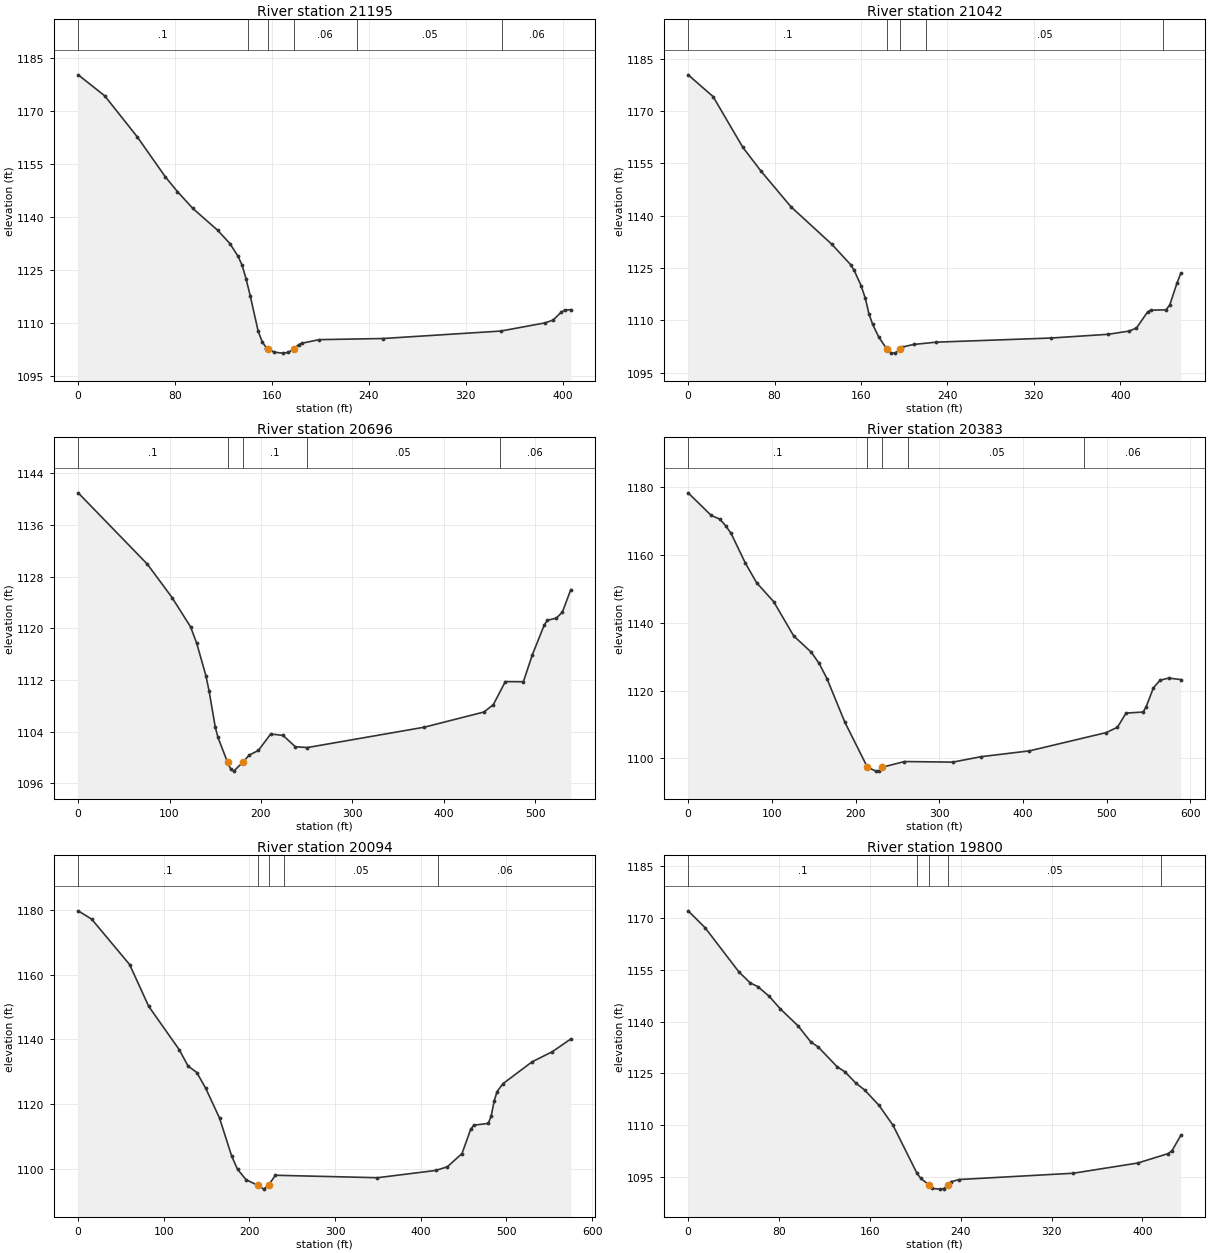
Type RM Length L Ch R = 1 ,21195   ,152.4,153.6,154.5
XS GIS Cut Line= 2
1676081.77092329  492442.81908141676008.08551568492842.752473086
#Sta/Elev= 30
       0 1180.37    21.9 1174.43    48.6 1162.88    71.9  1151.5    81.9 1147.31
    94.7 1142.51   115.3 1136.29   125.3 1132.56     132 1128.95   135.3 1126.45
   138.6 1122.59     142 1117.85   148.6 1107.73     152 1104.68   155.3 1103.08
   156.71102.746     162 1101.79   168.7 1101.53   173.6 1101.73  178.051102.747
     182 1103.94   184.8 1104.34   198.9 1105.35   251.5 1105.67   348.8 1107.78
   385.5  1110.1   392.2 1110.92   398.8 1113.16   401.7 1113.69   406.7 1113.84
#Mann= 6, -1 ,  0
       0     0.1       0     140    0.06       0   156.7   0.045       0
  178.05    0.06       0     230    0.05       0     350    0.06       0
Bank Sta=156.7,178.05
XS Rating Curve= 0 ,0
Exp/Cntr(USF)=0,0
Exp/Cntr=0.3,0.1

Type RM Length L Ch R = 1 ,21042   ,342.4,345.9,338.3
XS GIS Cut Line= 2
1675959.13068095492399.6526974371675823.45643078492834.976496843
#Sta/Elev= 30
       0 1180.42    23.1 1174.18    50.6 1159.64    67.7 1152.71    95.3 1142.54
     133 1131.83   150.3 1126.02   153.7 1124.33     160    1120     164 1116.36
   167.4 1111.83   170.8 1108.85   176.5 1105.19  183.791101.844     188 1100.64
   191.5 1100.61  196.521101.842   198.3 1102.36   208.6 1103.09   229.3 1103.75
   335.8 1104.94   388.8 1106.01     408 1106.93     415 1107.81   425.4 1112.49
   428.6 1112.92   442.3 1113.03   445.8 1114.43   452.6 1120.81     456 1123.49
#Mann= 5, -1 ,  0
       0     0.1       0  183.79   0.045       0  196.52     0.1       0
     220    0.05       0     440    0.06       0
Bank Sta=183.79,196.52
XS Rating Curve= 0 ,0
Exp/Cntr(USF)=0,0
Exp/Cntr=0.3,0.1

Type RM Length L Ch R = 1 ,20696   ,313.2,312.3,303.5
XS GIS Cut Line= 3
 1675667.0768887492305.3123149411675586.01522289492646.934166358
1675598.82976447492834.353404629
#Sta/Elev= 30
       0 1140.95    75.8  1129.9   102.7 1124.76     123 1120.22   129.7 1117.68
   139.8 1112.65   143.2 1110.34   149.9 1104.79   152.9 1103.15  163.391099.294
   166.8 1098.26   170.2 1097.91  180.311099.293     187 1100.38   197.2 1101.11
   210.6 1103.65   224.1 1103.44   237.6 1101.68   250.9 1101.56   378.5  1104.7
   443.9 1107.05   454.2 1108.18   467.3 1111.75   487.1 1111.73   496.9  1115.9
   510.1 1120.56   513.4 1121.24   523.2 1121.57   529.8 1122.51     539 1125.99
#Mann= 5, -1 ,  0
       0     0.1       0  163.39   0.045       0  180.31     0.1       0
     250    0.05       0  461.11    0.06       0
Bank Sta=163.39,180.31
XS Rating Curve= 0 ,0
Exp/Cntr(USF)=0,0
Exp/Cntr=0.3,0.1

Type RM Length L Ch R = 1 ,20383   ,288.9,289.2,288.3
XS GIS Cut Line= 3
1675279.36168994492237.447892118 1675295.0953574492298.530406507
1675429.37515737 492806.36776697
#Sta/Elev= 30
       0  1178.4    27.6 1171.72    37.8 1170.64    44.9 1168.66    51.3 1166.41
    68.3 1157.68    81.9 1151.82   102.2 1146.26     126 1136.19     147 1131.37
   156.5 1128.03   165.8 1123.56   187.2 1110.68  214.16 1097.38   224.4 1096.25
   227.8 1096.41  231.611097.382   258.3 1099.08   316.1 1098.91     350 1100.52
   407.6 1102.23   499.3 1107.62   512.8 1109.21     523 1113.38   543.4  1113.7
   546.8 1115.09   555.8 1120.89   563.7 1123.08   573.9 1123.72   588.4 1123.28
#Mann= 5, -1 ,  0
       0     0.1       0  214.16   0.045       0  231.61     0.1       0
  263.08    0.05       0  473.08    0.06       0
Bank Sta=214.16,231.61
XS Rating Curve= 0 ,0
Exp/Cntr(USF)=0,0
Exp/Cntr=0.3,0.1

Type RM Length L Ch R = 1 ,20094   ,291.7,294.2,293
XS GIS Cut Line= 2
1675008.00975992492317.8598220941675161.46275937492872.141688963
#Sta/Elev= 30
       0 1179.72    15.8 1177.14    60.1 1163.09    82.3 1150.19   117.9  1136.8
   128.2 1131.75   138.5  1129.7     149 1124.76     165 1115.62   179.2 1103.85
     186 1099.78   196.2 1096.49  209.351094.874   216.7 1093.63   222.21094.873
   230.3 1097.92   349.4 1097.16   417.5 1099.41   431.1 1100.56   448.1 1104.65
   458.2 1112.14   461.8  1113.4   478.8 1113.97   482.2 1116.31   485.6 1120.86
     489  1123.8   495.8 1126.22   529.8    1133   553.7 1136.17   575.1 1140.08
#Mann= 5, -1 ,  0
       0     0.1       0  209.35   0.045       0   222.2     0.1       0
     240    0.05       0     420    0.06       0
Bank Sta=209.35,222.2
XS Rating Curve= 0 ,0
Exp/Cntr(USF)=0,0
Exp/Cntr=0.3,0.1

Type RM Length L Ch R = 1 ,19800   ,298.1,301,301.8
XS GIS Cut Line= 6
1674756.06669426492380.6946701711674769.57421318 492472.04619351
 1674784.9518071492549.5279939171674805.21193717492647.453979179
1674820.40711676492720.8980580121674838.13477159492806.583254084
#Sta/Elev= 30
       0 1171.99    14.9 1167.12    44.7 1154.34    54.7 1151.15    61.3 1150.11
    71.3 1147.32    81.2 1143.65    96.7 1138.78   107.9 1134.16   114.6 1132.62
   131.3  1126.9     138 1125.49     148 1122.11   155.3 1120.26   168.1 1115.77
   180.4 1110.02   201.6 1096.09   204.9 1094.66  212.351092.737     215 1091.76
   221.7 1091.57     225 1091.72  228.821092.736   231.7  1093.7   238.4 1094.34
     339 1096.16   395.9 1099.11   422.7 1101.84   426.1  1102.7   433.8 1107.09
#Mann= 5, -1 ,  0
       0     0.1       0  201.34    0.05       0  212.35   0.045       0
  228.82    0.05       0  416.34    0.06       0
Bank Sta=212.35,228.82
XS Rating Curve= 0 ,0
Exp/Cntr(USF)=0,0
Exp/Cntr=0.3,0.1

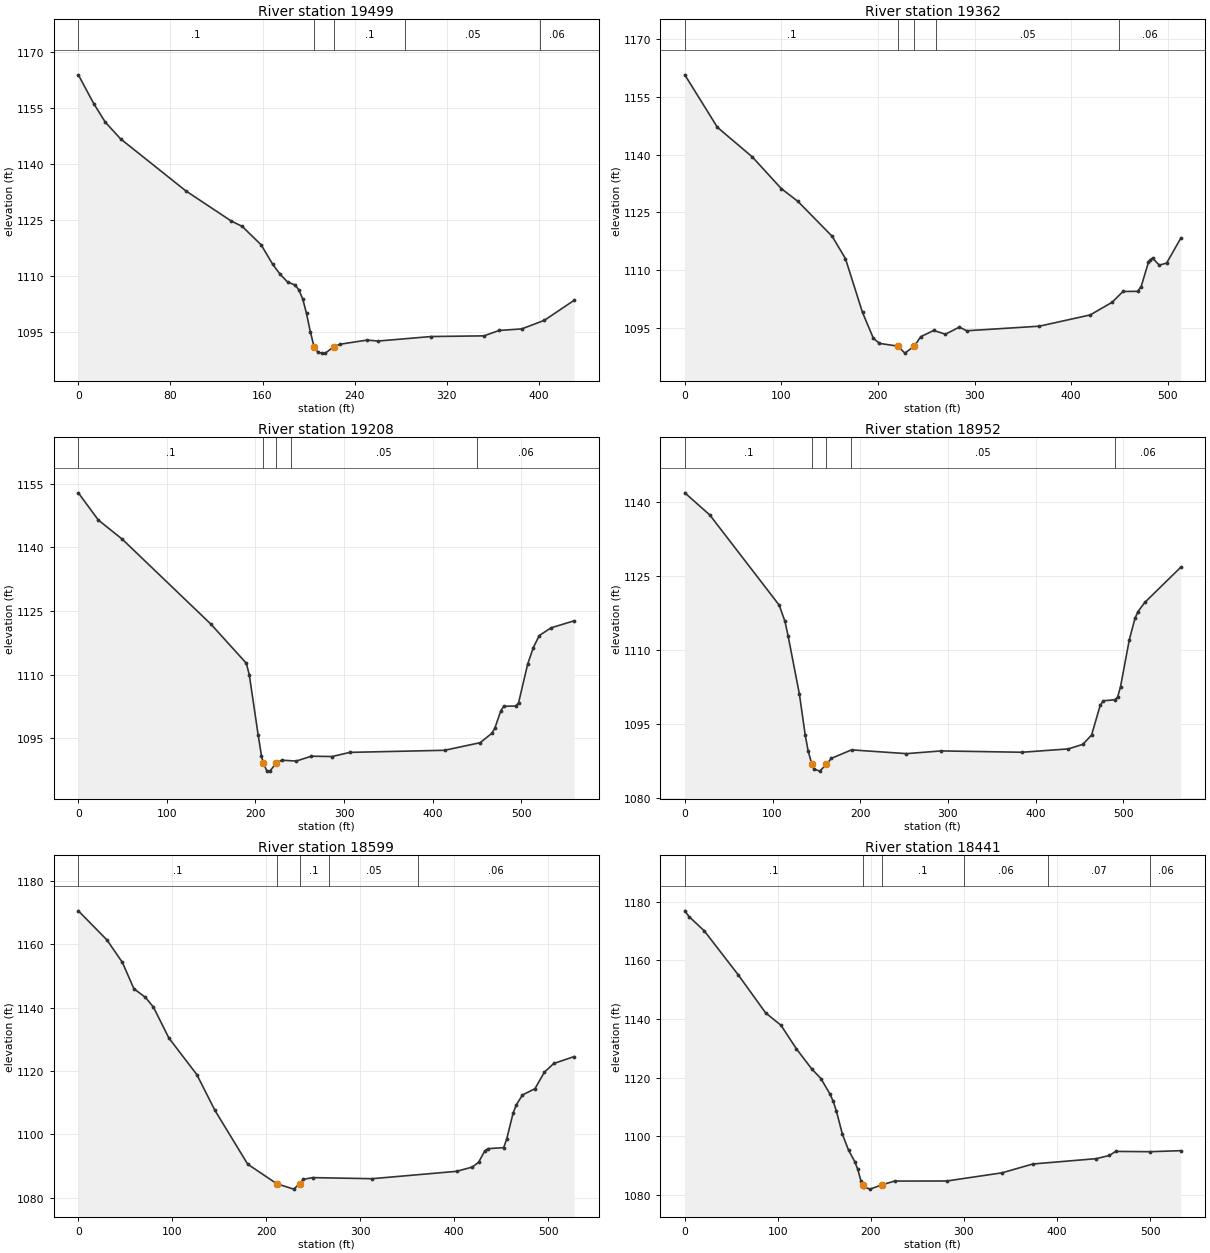
Type RM Length L Ch R = 1 ,19499   ,131,136.8,139.3
XS GIS Cut Line= 6
1674516.68790792492359.2134139241674502.14594226492446.302478582
1674502.14594226492521.3026566651674500.04555276492621.743400678
1674500.92547226492699.169755012  1674502.751256492788.709602177
#Sta/Elev= 30
       0    1164    13.4 1156.26    23.4 1151.29    36.7 1146.79    93.2 1132.86
   132.6 1124.76   142.4 1123.26   158.8 1118.32   168.7 1113.16   175.2 1110.44
   181.8 1108.32   188.3 1107.52   191.6 1106.18   194.9  1103.8   198.2 1099.88
   201.5 1094.99  204.771090.945     208 1089.48   211.3 1089.22   214.6 1089.23
  221.911090.943   227.7 1091.63   250.7 1092.72   260.5 1092.47   306.5 1093.68
   352.4 1093.86   365.5 1095.31   385.2 1095.73   404.9 1098.05   430.7 1103.42
#Mann= 5, -1 ,  0
       0     0.1       0  204.77   0.045       0  221.91     0.1       0
  283.76    0.05       0  401.19    0.06       0
Bank Sta=204.77,221.91
XS Rating Curve= 0 ,0
Exp/Cntr(USF)=0,0
Exp/Cntr=0.3,0.1

Type RM Length L Ch R = 1 ,19362   ,153.7,154.5,149.1
XS GIS Cut Line= 2
1674492.01267739492347.7109552391674240.40015461492795.269513474
#Sta/Elev= 30
       0 1160.75    33.8 1147.08    69.8 1139.42    99.9 1131.15   117.1 1127.83
   152.6 1118.73   166.3 1112.96     184 1098.93   195.2 1092.24   201.5 1090.88
  220.631090.157   227.9 1088.34   237.6 1090.16   244.3 1092.62   257.7 1094.23
   269.9 1093.27   284.3 1095.11   291.9 1094.16   367.1 1095.35   419.8 1098.28
   442.4 1101.56   453.7 1104.38   468.8 1104.42   472.5 1105.63     480 1111.93
   481.9 1112.59   484.3 1113.08   491.3 1111.23   498.9 1111.77   513.4 1118.18
#Mann= 5, -1 ,  0
       0     0.1       0  220.63   0.045       0   237.6     0.1       0
     260    0.05       0     450    0.06       0
Bank Sta=220.63,237.6
XS Rating Curve= 0 ,0
Exp/Cntr(USF)=0,0
Exp/Cntr=0.3,0.1

Type RM Length L Ch R = 1 ,19208   ,257.2,255.6,252
XS GIS Cut Line= 2
1674300.15389217492251.8222245131674194.76666922492801.650822277
#Sta/Elev= 30
       0 1152.86    22.6 1146.44    49.4 1141.97   149.6 1121.93   189.7 1112.69
     193 1109.98     203 1095.84   206.8 1090.87  208.691089.202     213 1087.27
   216.4 1087.32  223.691089.205   229.7 1089.84   246.1 1089.65   263.1 1090.79
   286.5 1090.71   306.6 1091.69   413.5 1092.18   453.6 1093.97   466.9 1096.19
   470.3 1097.43   476.9 1101.44   480.3 1102.55   493.6 1102.62     497 1103.34
   507.3 1112.49   513.7 1116.38   520.4 1119.23   533.7 1121.04   559.8  1122.7
#Mann= 5, -1 ,  0
       0     0.1       0  208.69   0.045       0  223.69     0.1       0
     240    0.05       0     450    0.06       0
Bank Sta=208.69,223.69
XS Rating Curve= 0 ,0
Exp/Cntr(USF)=0,0
Exp/Cntr=0.3,0.1

Type RM Length L Ch R = 1 ,18952   ,350.2,352.8,350.4
XS GIS Cut Line= 2
1674002.41196448492239.1505077311674060.15435486492801.482840511
#Sta/Elev= 30
       0 1141.78    28.5  1137.3   107.6 1119.06   114.2 1115.77   117.8 1112.81
   130.7 1101.01   137.3 1092.77   140.6 1089.57  144.971086.819   147.2  1085.9
   153.8 1085.47  161.421086.818     167 1088.05   190.1 1089.77   252.7 1089.01
   292.3 1089.56   384.7 1089.29   437.4 1089.97   453.9 1090.89   463.8 1092.79
   473.7 1098.82     477  1099.7   490.2 1099.91   493.5 1100.45   496.8 1102.57
   506.8 1112.06   513.3  1116.4   516.6 1117.73   524.5 1119.61   565.3  1126.7
#Mann= 5, -1 ,  0
       0     0.1       0  144.97   0.045       0  161.42     0.1       0
     190    0.05       0     490    0.06       0
Bank Sta=144.97,161.42
XS Rating Curve= 0 ,0
Exp/Cntr(USF)=0,0
Exp/Cntr=0.3,0.1

Type RM Length L Ch R = 1 ,18599   ,153,157.9,156.8
XS GIS Cut Line= 6
1673672.69254868492309.2984874991673680.74043284492403.518443421
1673691.33194709492484.6432811771673710.58551751492583.081076428
1673723.77085859492656.9129497561673754.90950956492830.162146138
#Sta/Elev= 30
       0 1170.53    30.5 1161.33    46.9 1154.25    59.1 1145.96    71.3 1143.25
    79.9 1140.18    96.3 1130.43   126.1 1118.87   145.3 1107.62   180.2 1090.61
  211.221084.419   229.2 1082.72   235.6 1084.42   239.3 1085.79   249.3 1086.35
   312.7 1086.01   402.7 1088.34   419.4  1089.7     426 1091.19   432.7 1094.85
     436 1095.49   452.7 1095.81     456 1098.61   462.7  1106.7     466 1109.24
   472.7 1112.43     486 1114.41     496 1119.61     506 1122.36   527.7 1124.54
#Mann= 5, -1 ,  0
       0     0.1       0  211.22   0.045       0   235.6     0.1       0
  266.38    0.05       0  361.68    0.06       0
Bank Sta=211.22,235.6
XS Rating Curve= 0 ,0
Exp/Cntr(USF)=0,0
Exp/Cntr=0.3,0.1

Type RM Length L Ch R = 1 ,18441   ,146.2,151.9,148.9
XS GIS Cut Line= 2
1673529.75107046492308.9829062841673585.75267005492838.969058987
#Sta/Elev= 30
       0 1176.92     4.5 1174.97      21 1170.06    57.2 1155.16    86.9 1142.07
   103.4 1137.84   119.9 1129.83   136.4 1122.96   146.3 1119.65   156.2 1114.27
   159.5 1111.87   162.8  1108.7   169.4 1100.64     176  1095.2   182.6 1091.33
   185.9 1088.68   189.2 1084.84  191.431083.374   192.5 1082.67   199.1  1081.9
  211.831083.377   225.5 1084.65   281.6 1084.68     341 1087.47     374 1090.48
   442.1  1092.3   456.4 1093.39     463 1094.78     500 1094.68   532.9 1095.03
#Mann= 6, -1 ,  0
       0     0.1       0  191.43   0.045       0  211.83     0.1       0
     300    0.06       0     390    0.07       0     500    0.06       0
Bank Sta=191.43,211.83
XS Rating Curve= 0 ,0
Exp/Cntr(USF)=0,0
Exp/Cntr=0.3,0.1

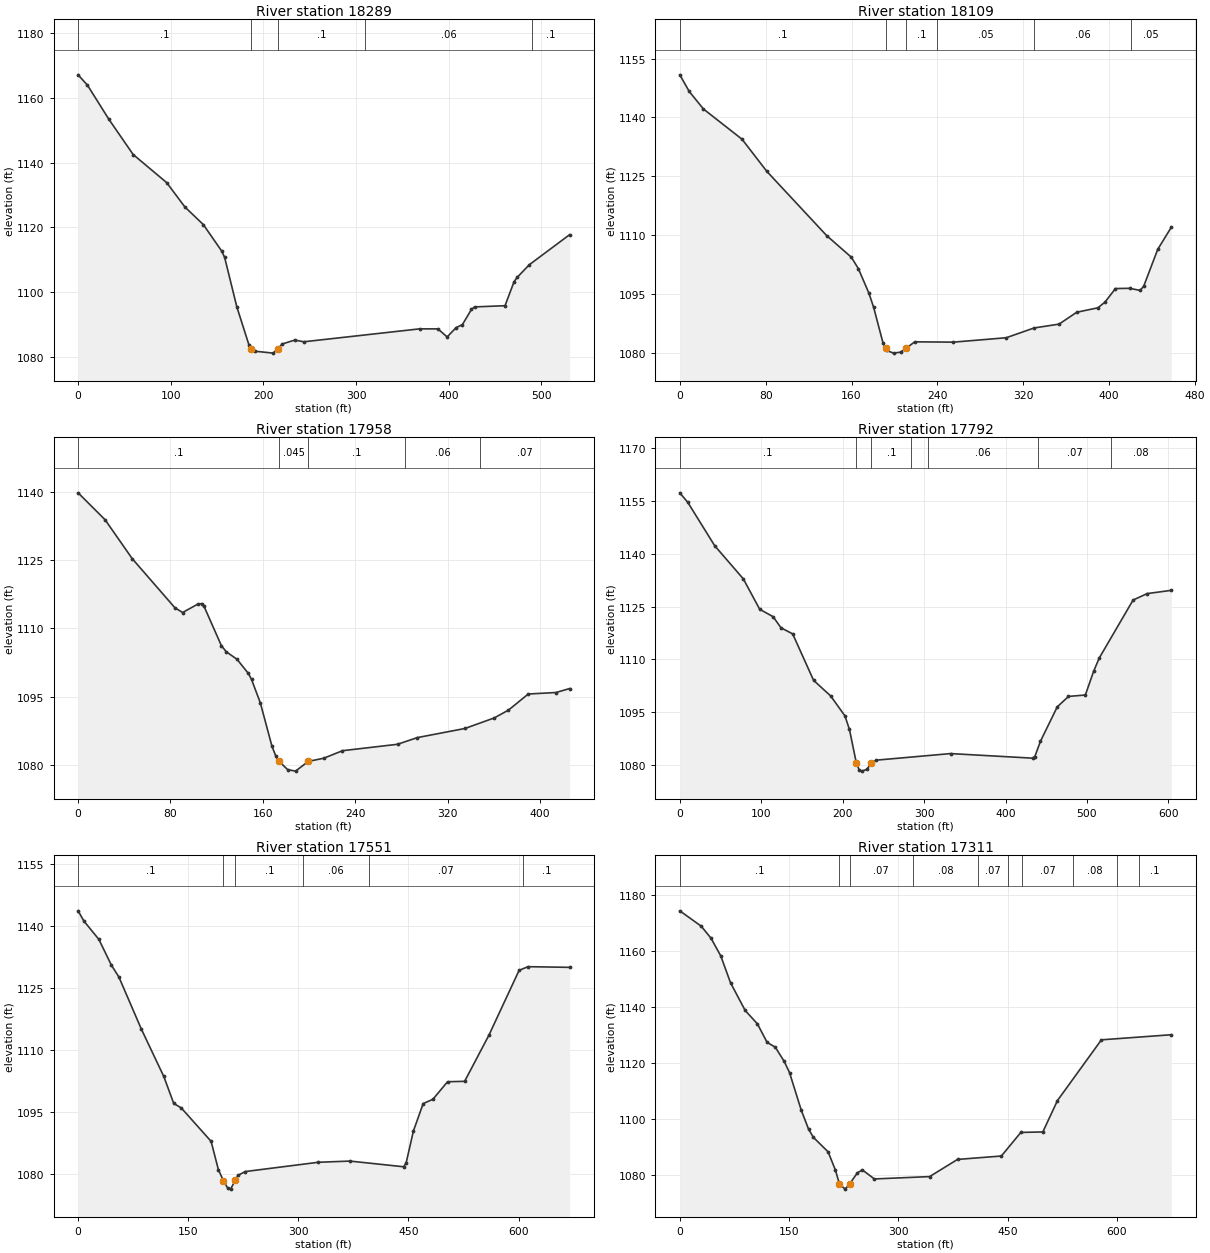
Type RM Length L Ch R = 1 ,18289   ,178.7,180.6,180.8
XS GIS Cut Line= 2
1673397.52710297492332.8855674661673436.28532907492861.941984107
#Sta/Elev= 30
       0  1167.2    10.1 1163.99    33.1 1153.49    59.4 1142.55    95.6 1133.85
   115.3  1126.3   135.1 1120.89   154.8 1112.75   158.1 1110.78   171.3 1095.43
   184.4 1083.63  186.561082.487   190.6  1081.7   210.7  1081.1  215.491082.489
   220.6 1083.95   233.8 1085.14   243.6 1084.61   368.6 1088.61   388.4  1088.6
   398.3 1086.11   408.1 1089.02   414.7 1089.87   424.6 1094.65   427.9  1095.4
   460.8 1095.77   470.6 1103.22   473.9 1104.53   487.1 1108.47   530.5 1117.74
#Mann= 5, -1 ,  0
       0     0.1       0  186.56   0.045       0  215.49     0.1       0
     310    0.06       0     490     0.1       0
Bank Sta=186.56,215.49
XS Rating Curve= 0 ,0
Exp/Cntr(USF)=0,0
Exp/Cntr=0.3,0.1

Type RM Length L Ch R = 1 ,18109   ,147.9,150.7,153.5
XS GIS Cut Line= 2
1673235.94557692492337.3895147751673233.51072477492795.141720172
#Sta/Elev= 30
       0 1150.85     8.8 1146.61      22 1142.15      58 1134.44      81 1126.28
   136.8  1109.9   159.8 1104.39   166.3  1101.5   176.2 1095.21   180.6 1091.59
   189.3 1082.55  191.611081.227   192.6 1080.66   199.1 1079.96   205.7 1080.21
  211.041081.227   218.8 1082.84   254.9 1082.76   304.1 1083.88     330 1086.37
   353.3 1087.35   369.7 1090.37   389.4  1091.5     396 1092.93   405.8 1096.41
   418.9 1096.47   428.8 1095.94   432.1 1096.99   445.2  1106.4   457.8 1112.01
#Mann= 6, -1 ,  0
       0     0.1       0  191.61   0.045       0  211.04     0.1       0
     240    0.05       0     330    0.06       0     420    0.05       0
Bank Sta=191.61,211.04
XS Rating Curve= 0 ,0
Exp/Cntr(USF)=0,0
Exp/Cntr=0.3,0.1

Type RM Length L Ch R = 1 ,17958   ,164.4,166.4,167.6
XS GIS Cut Line= 6
1673127.48697292492333.2181561011673109.04967383492419.133666681
1673092.46112433492492.5062233531673066.66130716492589.182867261
1673044.82440858492660.9333799351673019.34644117492744.642202021
#Sta/Elev= 30
       0  1139.8    23.4 1133.87    46.9 1125.32    83.8 1114.55    90.5 1113.49
   103.9 1115.37   107.3 1115.44   109.1 1114.83   124.1 1106.21   128.3 1104.87
   137.6 1103.22   147.5 1100.09   150.2 1098.79   157.8 1093.66   167.9 1084.11
   171.3 1081.89  174.111080.772   181.5 1078.96   188.3 1078.63  199.431080.772
   212.7 1081.46     229 1083.12   276.7 1084.53   293.8    1086     335    1088
   360.4 1090.32   372.7 1092.03   389.9 1095.58   413.9 1095.91   425.7 1096.78
#Mann= 5, -1 ,  0
       0     0.1       0  174.11   0.045       0  199.43     0.1       0
  283.16    0.06       0  348.16    0.07       0
Bank Sta=174.11,199.43
XS Rating Curve= 0 ,0
Exp/Cntr(USF)=0,0
Exp/Cntr=0.3,0.1

Type RM Length L Ch R = 1 ,17792   ,240.5,240.4,237.2
XS GIS Cut Line= 6
1673034.71267892492235.8025025561672994.63500318 492314.55103272
1672960.34242084492382.2749786361672925.73455043492476.297100304
1672898.78841009492546.4797027091672818.13226104492797.716844499
#Sta/Elev= 30
       0 1157.37     9.8 1154.66    42.9 1142.31      78  1132.9    98.1 1124.26
   114.6 1122.13   124.3 1118.97   138.6 1117.25   164.3 1104.03   185.3 1099.59
   202.8 1093.91   208.3 1090.09   216.8 1080.51   220.2 1078.61   223.7 1078.21
   229.8 1078.72   234.9 1080.41   241.2 1081.33   332.5  1083.2   433.1  1081.9
     436 1082.37   442.9 1086.73   463.5 1096.49   477.3 1099.46     498 1099.86
   508.3 1106.69   515.2 1110.44   556.6 1126.87   573.9 1128.71   603.5 1129.63
#Mann= 7, -1 ,  0
       0     0.1       0   216.8   0.045       0   234.9     0.1       0
  284.46    0.05       0  304.46    0.06       0  439.64    0.07       0
  529.64    0.08       0
Bank Sta=216.8,234.9
XS Rating Curve= 0 ,0
Exp/Cntr(USF)=0,0
Exp/Cntr=0.3,0.1

Type RM Length L Ch R = 1 ,17551   ,242.1,240.3,236.3
XS GIS Cut Line= 3
 1672679.5511298492158.1757393641672725.84992692492328.555312739
1672648.99392371492815.618658365
#Sta/Elev= 30
       0 1143.76     7.9 1141.28    28.3 1136.83    45.3  1130.6    55.5 1127.74
    86.1 1115.11   116.7 1103.62   130.3 1097.07   140.5 1095.99   181.2 1087.88
   191.1 1081.02197.93581078.359   203.9  1076.5   207.7  1076.3214.32661078.498
   217.7 1079.63   227.7 1080.56   327.3 1082.81   370.3  1083.1   443.5 1081.72
   446.9 1082.64   456.8 1090.38   470.1 1097.03   483.4 1098.08   503.3 1102.33
   526.6 1102.43   559.7 1113.62   600.8 1129.33   612.9 1130.22   669.6 1130.06
#Mann= 6, -1 ,  0
       0     0.1       0197.9358   0.045       0214.3266     0.1       0
  306.56    0.06       0  396.56    0.07       0  606.56     0.1       0
Bank Sta=197.9358,214.3266
XS Rating Curve= 0 ,0
Exp/Cntr(USF)=0,0
Exp/Cntr=0.3,0.1

Type RM Length L Ch R = 1 ,17311   ,362.8,362.8,358.2
XS GIS Cut Line= 2
1672441.92911039492173.0425484411672577.39861928492833.875092495
#Sta/Elev= 30
       0 1174.38    29.4 1168.89    42.8 1164.61    56.2 1158.28    69.6 1148.68
    89.7 1138.76   106.5 1133.97   119.8 1127.36   131.1 1125.61   143.3 1120.55
   150.6 1116.53   166.7 1103.11   176.8 1096.27   183.5 1093.34   203.6 1088.19
   213.6 1081.67  219.12  1076.7     227 1074.86  233.031076.697   243.8 1080.68
   250.5 1081.75   267.1  1078.5   342.9 1079.34   381.2 1085.48   441.4  1086.7
   468.1 1095.14   498.3 1095.31   518.4 1106.54   578.7 1128.25   674.6 1130.07
#Mann= 10, -1 ,  0
       0     0.1       0  219.12   0.045       0  233.03    0.07       0
     320    0.08       0     410    0.07       0     450    0.08       0
     470    0.07       0     540    0.08       0     600    0.07       0
     630     0.1       0
Bank Sta=219.12,233.03
XS Rating Curve= 0 ,0
Exp/Cntr(USF)=0,0
Exp/Cntr=0.3,0.1

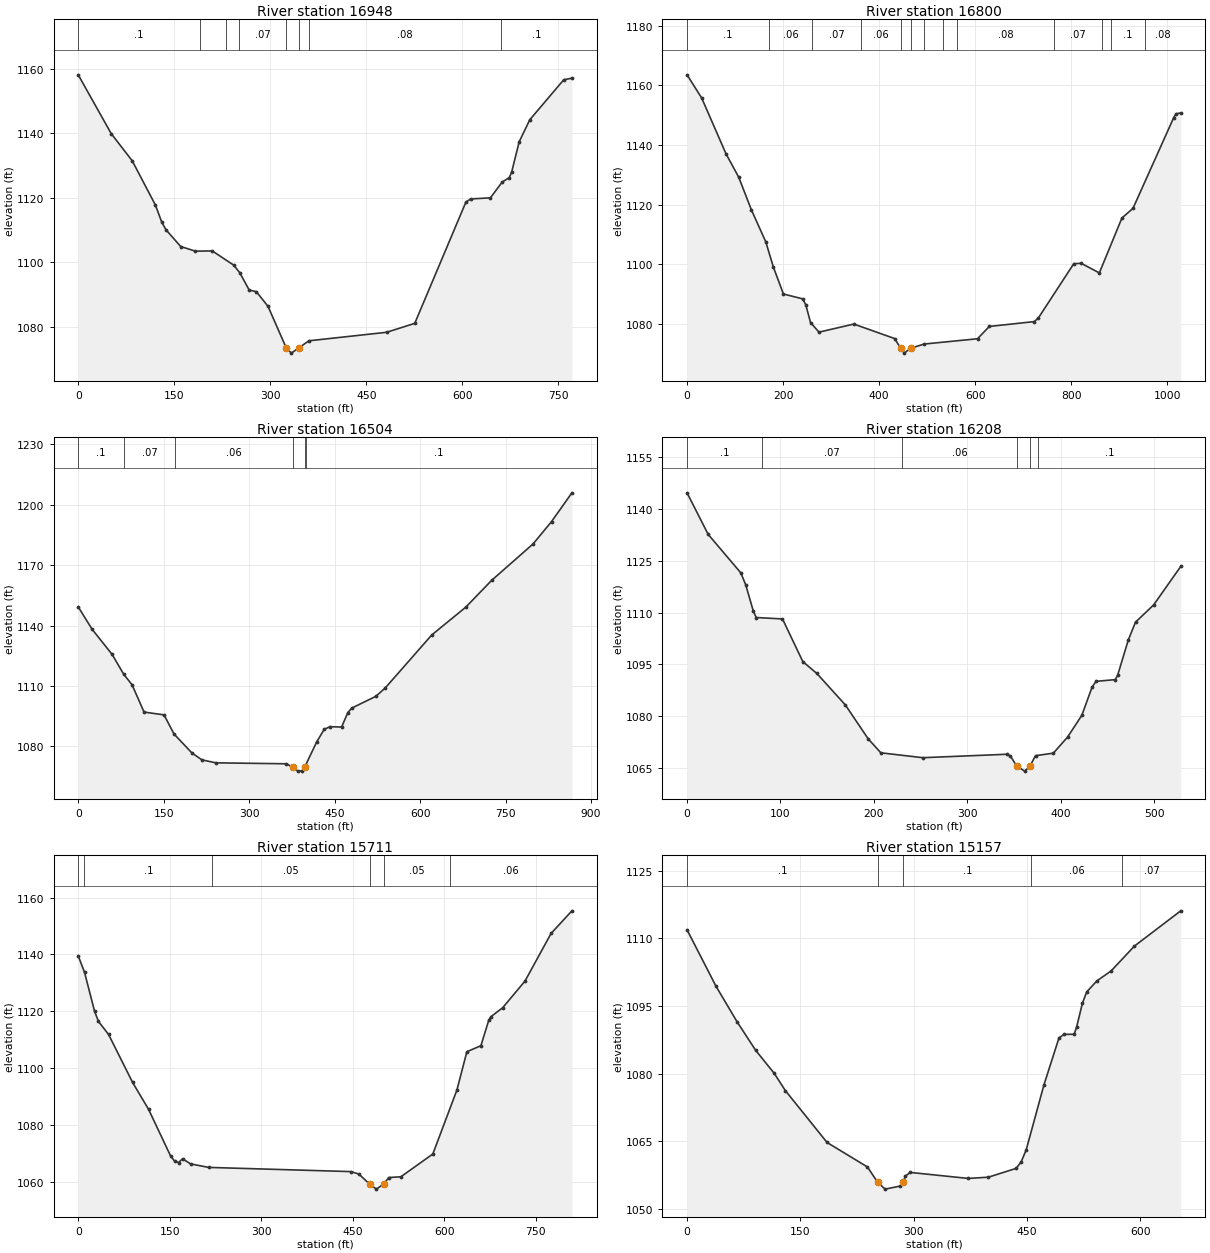
Type RM Length L Ch R = 1 ,16948   ,147.6,148.3,148.1
XS GIS Cut Line= 3
1672094.78028434492206.2323877491672109.94508924492426.302510672
1672362.90584687492915.322161014
#Sta/Elev= 30
       0  1158.2    51.5 1139.96    84.4  1131.5   120.6 1117.77   130.5 1112.47
     137 1110.13   160.1 1104.91   183.1 1103.47   209.4 1103.54   242.9 1099.13
   252.3 1096.79   267.1 1091.39   278.2  1090.9   296.5 1086.34  325.021073.405
     333 1071.82  344.211073.403   360.4 1075.65   481.8 1078.29   525.7 1081.06
   605.6  1118.7   612.9 1119.67   643.9 1120.02   662.3 1124.92   673.4  1126.3
   677.1 1128.03   688.8  1137.4   705.4 1144.25   758.4 1156.66   771.2 1157.16
#Mann= 8, -1 ,  0
       0     0.1       0     190    0.07       0  230.59     0.1       0
  250.59    0.07       0  325.02   0.045       0  344.21    0.07       0
  360.59    0.08       0  660.59     0.1       0
Bank Sta=325.02,344.21
XS Rating Curve= 0 ,0
Exp/Cntr(USF)=0,0
Exp/Cntr=0.3,0.1

Type RM Length L Ch R = 1 ,16800   ,288.2,296.2,304.3
XS GIS Cut Line= 3
 1671981.5084212 492138.296912211671940.11021503 492397.96114288
1672265.64853171493090.048986044
#Sta/Elev= 30
       0 1163.58    30.5 1155.79      81 1137.12   107.6 1129.22   134.1 1118.22
     164 1107.52   179.5 1099.18   200.6 1090.05   240.5 1088.42   247.1  1086.5
   257.1 1080.46   274.7 1077.25   347.2 1079.96     432 1075.11     4451071.834
   452.3 1070.21  465.391071.833   493.7 1073.26   604.7 1075.03   629.3 1079.16
     723 1080.79   731.5 1082.03   805.1 1100.21   820.5 1100.34   858.4 1097.13
   905.3 1115.52   928.5 1118.81  1013.2 1149.23  1017.9  1150.5  1027.8  1150.8
#Mann= 13, -1 ,  0
       0     0.1       0     170    0.06       0     260    0.07       0
  362.94    0.06       0     445   0.045       0  465.39    0.07       0
  492.94    0.06       0  532.94    0.07       0  562.94    0.08       0
  762.94    0.07       0  862.94    0.08       0  882.94     0.1       0
  952.94    0.08       0
Bank Sta=445,465.39
XS Rating Curve= 0 ,0
Exp/Cntr(USF)=0,0
Exp/Cntr=0.3,0.1

Type RM Length L Ch R = 1 ,16504   ,292.2,295.4,296.4
XS GIS Cut Line= 2
1671887.36912983492146.2434304481671581.92887006492956.979922424
#Sta/Elev= 30
       0 1149.29    24.3  1138.2    59.4 1125.72    79.9  1115.8    94.5  1110.6
   115.5 1097.05   150.6 1095.66   168.1 1086.16   199.7  1076.7   217.2  1073.3
   241.7 1071.84   365.5 1071.37  377.321069.531   385.5 1067.72   392.5 1067.87
  397.151069.531   418.3 1082.11   431.7 1088.48   441.6 1089.78   462.3 1089.63
   473.1 1096.77     480 1099.01   522.2 1104.86   538.7 1108.99   620.4 1135.34
     680 1149.12   725.6 1162.48   798.4  1180.6   830.7 1191.68   866.4 1205.94
#Mann= 6, -1 ,  0
       0     0.1       0      80    0.07       0     170    0.06       0
  377.32   0.045       0  397.15    0.06       0     400     0.1       0
Bank Sta=377.32,397.15
XS Rating Curve= 0 ,0
Exp/Cntr(USF)=0,0
Exp/Cntr=0.3,0.1

Type RM Length L Ch R = 1 ,16208   ,502.6,497.2,491.7
XS GIS Cut Line= 6
1671710.86487061 492058.73079644 1671600.9309033492214.520274222
1671556.27679312492275.2051922081671502.91731979 492359.82871063
1671464.76122813492424.3974791321671418.92011246492498.944246054
#Sta/Elev= 30
       0 1144.58    22.6 1132.58    57.5 1121.49    62.8 1118.03    70.8 1110.56
      74 1108.56   102.2 1108.15     124 1095.81     139  1092.4   169.5 1083.31
     194  1073.5   207.5 1069.48   252.4 1068.07   342.2 1069.06   346.1 1068.62
  353.02 1065.62   361.6 1064.19  367.08 1065.62   373.1 1068.65   392.2 1069.38
   407.4 1074.01   422.7 1080.31   433.7 1088.47   437.9 1090.12   458.4 1090.62
     461 1091.84   472.5  1102.1   480.2 1107.23   499.5 1112.17   528.6 1123.31
#Mann= 6, -1 ,  0
       0     0.1       0      80    0.07       0  230.67    0.06       0
  353.02   0.045       0  367.08    0.06       0  376.06     0.1       0
Bank Sta=353.02,367.08
XS Rating Curve= 0 ,0
Exp/Cntr(USF)=0,0
Exp/Cntr=0.3,0.1

Type RM Length L Ch R = 1 ,15711   ,553.6,553.7,544.7
XS GIS Cut Line= 2
1671093.07152481491640.4269582011671067.62026476492449.397427275
#Sta/Elev= 30
       0 1139.48    10.3 1133.72    26.7 1120.08    33.2 1116.42    49.7 1111.88
      89 1095.05   115.3 1085.54   151.4 1069.16     158 1067.34   164.5 1066.84
   171.1 1068.15   184.2 1066.35   213.8 1065.12   446.8 1063.64     460  1062.8
  477.791059.245   488.8 1057.48  500.541059.245   509.2 1061.56   528.9 1061.81
   581.4 1069.83   620.8 1092.28   637.2 1105.79   660.2  1107.9   673.2 1116.94
   676.6  1118.1   695.7 1121.21   732.4  1130.6   775.2 1147.35   809.4 1155.32
#Mann= 6, -1 ,  0
       0    0.06       0      10     0.1       0     220    0.05       0
  477.79   0.045       0  500.54    0.05       0     610    0.06       0
Bank Sta=477.79,500.54
XS Rating Curve= 0 ,0
Exp/Cntr(USF)=0,0
Exp/Cntr=0.3,0.1

Type RM Length L Ch R = 1 ,15157   ,364.1,371.1,355.4
XS GIS Cut Line= 3
1670484.63010575491782.0210646921670549.17944044 491956.14565433
1670633.67368806492416.030425362
#Sta/Elev= 30
       0 1111.92    38.4 1099.39    66.2 1091.53    90.9 1085.19   115.4  1080.1
     130  1076.3   185.3 1064.78   238.7 1059.35  252.071055.999   262.1 1054.44
   282.1 1055.12  286.04    1056   288.8 1057.32   295.4 1058.14   372.2 1056.81
   398.8 1057.09   435.5 1059.04   442.2 1060.51   448.9 1063.19   472.2  1077.5
   492.2 1087.97   498.9 1088.74   512.3 1088.77   515.6 1090.42   523.2 1095.66
   528.9 1098.15   542.3  1100.6   561.1 1102.79     592 1108.31   653.3 1116.13
#Mann= 5, -1 ,  0
       0     0.1       0  252.07   0.045       0  286.04     0.1       0
   455.7    0.06       0   575.7    0.07       0
Bank Sta=252.07,286.04
XS Rating Curve= 0 ,0
Exp/Cntr(USF)=0,0
Exp/Cntr=0.3,0.1