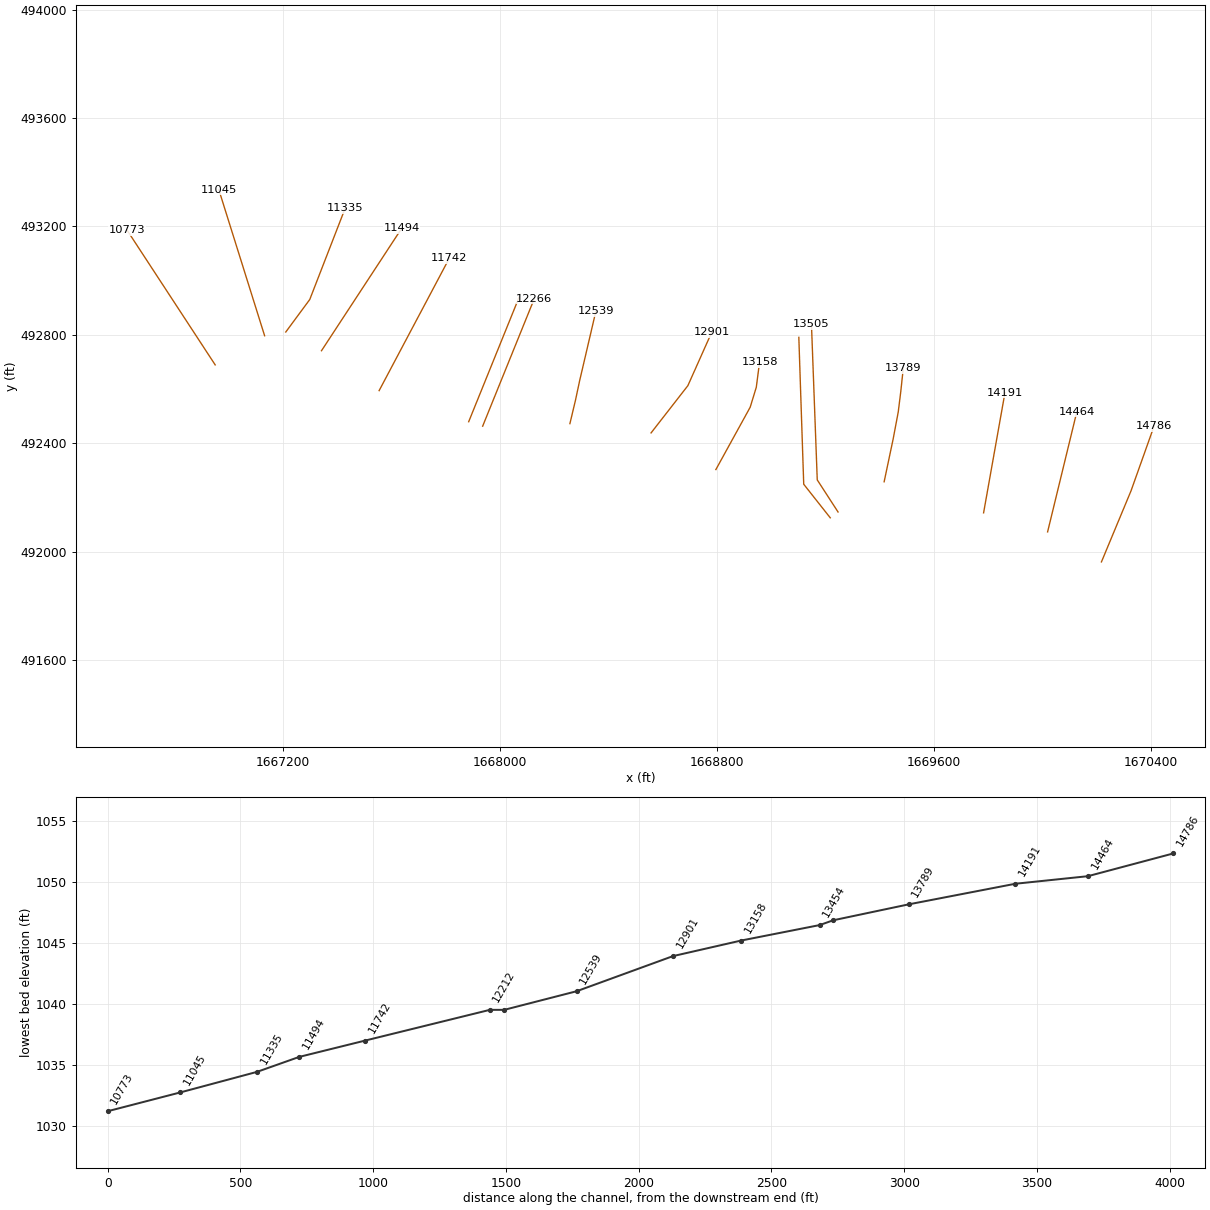
HEC-RAS study NFGraveCk.prj: NFGraveCk

--- NFGraveCk.g01 (geometry) --- (continued)

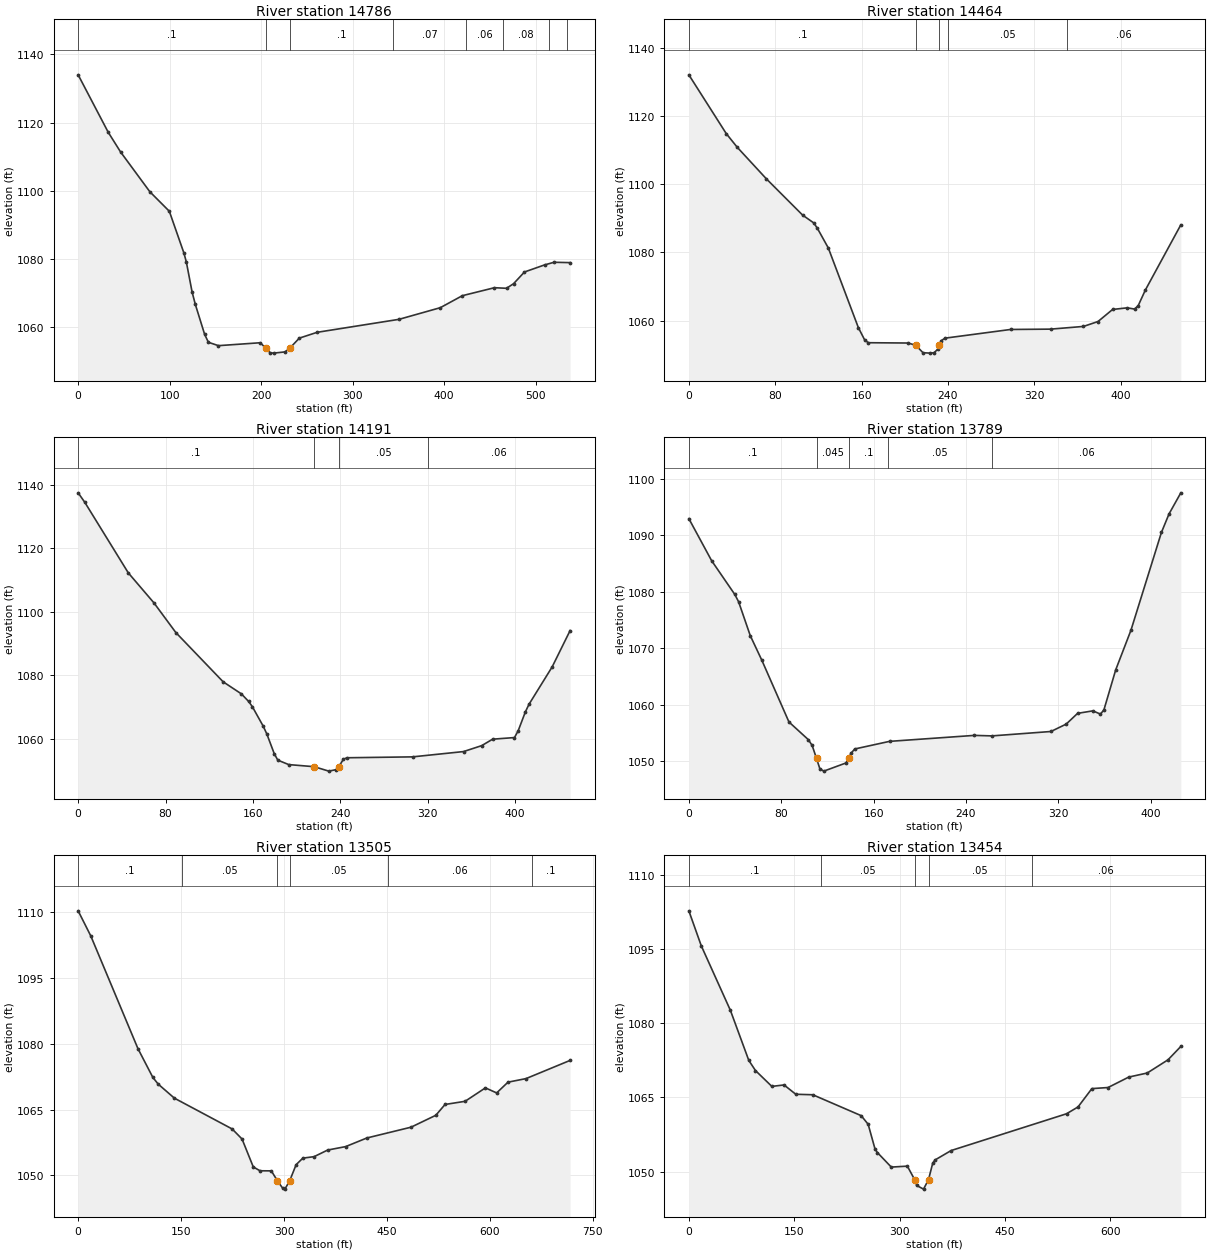
Type RM Length L Ch R = 1 ,14786   ,311,322.3,316.6
XS GIS Cut Line= 3
1670218.59813661491962.1614938291670327.75052412492224.581826627
 1670412.6840555492463.469657842
#Sta/Elev= 30
       0 1134.01    32.9 1117.15    46.4 1111.38    78.4 1099.71    99.7 1093.98
   115.6 1081.76   118.3 1079.09   124.6 1070.27   128.1 1066.67   138.3 1057.86
   142.4 1055.55   153.4 1054.56   199.2 1055.42  204.861053.861   209.9 1052.48
   213.6 1052.37   226.2 1052.73  231.491053.862   241.8 1056.77   261.3 1058.48
   350.7 1062.28   395.9  1065.7     420 1069.22   455.1 1071.56   468.3 1071.39
     476 1072.74   487.9 1076.17   509.9 1078.25   520.2 1079.02   537.8 1078.92
#Mann= 8, -1 ,  0
       0     0.1       0  204.86   0.045       0  231.49     0.1       0
  344.22    0.07       0  424.22    0.06       0  464.22    0.08       0
  514.22    0.06       0  534.22     0.1       0
Bank Sta=204.86,231.49
XS Rating Curve= 0 ,0
Exp/Cntr(USF)=0,0
Exp/Cntr=0.3,0.1

Type RM Length L Ch R = 1 ,14464   ,268.5,272.9,270.6
XS GIS Cut Line= 2
1670020.12217851492073.0804766361670127.80314188492515.861332719
#Sta/Elev= 30
       0 1132.03    34.6 1114.83    44.8 1110.81    71.8 1101.56   105.4 1090.93
   115.7 1088.64     119  1087.1   129.2 1081.29     157 1057.98   162.9 1054.33
   166.3 1053.55   203.2 1053.46  210.211052.786   216.9 1050.62   223.7  1050.5
   227.1 1050.62   230.5 1051.61  232.041052.789   233.8 1054.14   237.2 1054.88
     298 1057.43   335.1 1057.53   365.5 1058.32     379 1059.76   392.5 1063.29
     406 1063.77   412.8 1063.41   416.2 1064.39   422.9 1069.01   455.7 1088.08
#Mann= 5, -1 ,  0
       0     0.1       0  210.21   0.045       0  232.04     0.1       0
     240    0.05       0     350    0.06       0
Bank Sta=210.21,232.04
XS Rating Curve= 0 ,0
Exp/Cntr(USF)=0,0
Exp/Cntr=0.3,0.1

Type RM Length L Ch R = 1 ,14191   ,398.5,401.6,396.5
XS GIS Cut Line= 2
1669784.10124451492143.3683731711669862.89948062492586.657450963
#Sta/Elev= 30
       0 1137.53     6.1 1134.54    45.9 1112.32    69.4 1102.86    89.4 1093.53
   132.7 1078.01   149.4 1074.21     156 1071.83   159.4 1070.19   169.4 1064.02
   172.7 1061.56   179.4 1055.43   182.7 1053.34   192.7 1051.94  216.031051.274
   229.4 1049.88     236 1050.34   238.6 1051.27   242.7 1053.62     246 1054.09
     306 1054.37   352.7 1056.04   369.3 1057.91   379.3 1059.94   399.3 1060.45
   402.7  1062.6   409.3 1068.56   412.6 1070.94   433.8 1082.72   450.2 1094.15
#Mann= 4, -1 ,  0
       0     0.1       0  216.03   0.045       0   238.6    0.05       0
     320    0.06       0
Bank Sta=216.03,238.6
XS Rating Curve= 0 ,0
Exp/Cntr(USF)=0,0
Exp/Cntr=0.3,0.1

Type RM Length L Ch R = 1 ,13789   ,281.8,284.9,286.5
XS GIS Cut Line= 6
1669417.39637606 492258.07880208 1669435.4229148492343.701662333
1669450.87367131492417.0929197531669469.36411989492515.392263831
1669478.67053172492590.3048436651669488.07536855492677.936558173
#Sta/Elev= 30
       0 1092.98    19.7 1085.53    39.8 1079.53    43.1 1078.23    53.2 1072.22
    63.3 1067.82    86.7 1056.91   103.5 1053.77   106.8 1052.74  110.571050.438
   113.5 1048.59   116.9 1048.19   136.1 1049.64  138.441050.438   140.4 1051.35
   143.7 1052.12   173.8 1053.47   247.3 1054.53   262.5 1054.44   313.6 1055.22
   326.8 1056.53   336.7 1058.44   349.9 1058.88   356.5 1058.31   359.5 1059.06
   369.7 1066.15   382.9 1073.18   409.3 1090.53   415.9 1093.82   426.1 1097.56
#Mann= 5, -1 ,  0
       0     0.1       0  110.57   0.045       0  138.44     0.1       0
   172.5    0.05       0   262.5    0.06       0
Bank Sta=110.57,138.44
XS Rating Curve= 0 ,0
Exp/Cntr(USF)=0,0
Exp/Cntr=0.3,0.1

Type RM Length L Ch R = 1 ,13505   ,50.2,50.2,50.1
XS GIS Cut Line= 3
1669247.40042755492146.5663535941669170.75455755492264.869697379
1669149.33764126492840.354105682
#Sta/Elev= 30
       0 1110.29    18.4 1104.58    87.2 1078.87   108.9 1072.32   116.7  1070.8
   140.2 1067.61   224.4 1060.59   238.8  1058.3   255.2 1051.93     265 1051.06
   281.5 1051.04  290.351048.776   297.9 1047.12   301.2 1046.88  308.211048.774
   317.6 1052.45   327.4 1053.94   343.8 1054.28   363.5 1055.78   389.8 1056.57
   420.6 1058.53     485 1060.99   521.1  1063.7   534.6 1066.17   563.8 1066.89
   593.4 1069.95   609.8  1068.8   626.3 1071.25   652.5 1072.06   716.8 1076.21
#Mann= 6, -1 ,  0
       0     0.1       0  150.96    0.05       0  290.35   0.045       0
  308.21    0.05       0  450.96    0.06       0  660.96     0.1       0
Bank Sta=290.35,308.21
XS Rating Curve= 0 ,0
Exp/Cntr(USF)=0,0
Exp/Cntr=0.3,0.1

Type RM Length L Ch R = 1 ,13454   ,301.6,295.8,289.6
XS GIS Cut Line= 3
1669218.67262095492125.0551542491669120.87348577492248.925146768
1669102.79655871492791.009662666
#Sta/Elev= 30
       0 1102.67    17.7  1095.6    59.1 1082.59    85.3 1072.48    94.8 1070.43
   118.1 1067.23   135.5 1067.52   152.2 1065.64   176.4 1065.54   245.3 1061.32
   255.2 1059.58     265 1054.57   268.3 1053.88   288.1 1050.94     311 1051.13
  321.371048.403   324.1 1047.24     334 1046.49  341.091048.404   347.1 1051.73
   350.4 1052.38   373.3 1054.28   537.5  1061.7   553.9 1063.08   573.6 1066.78
   596.6    1067   626.1 1069.11   652.4 1069.93     682  1072.6   700.2 1075.29
#Mann= 5, -1 ,  0
       0     0.1       0  187.82    0.05       0  321.37   0.045       0
  341.09    0.05       0  487.82    0.06       0
Bank Sta=321.37,341.09
XS Rating Curve= 0 ,0
Exp/Cntr(USF)=0,0
Exp/Cntr=0.3,0.1

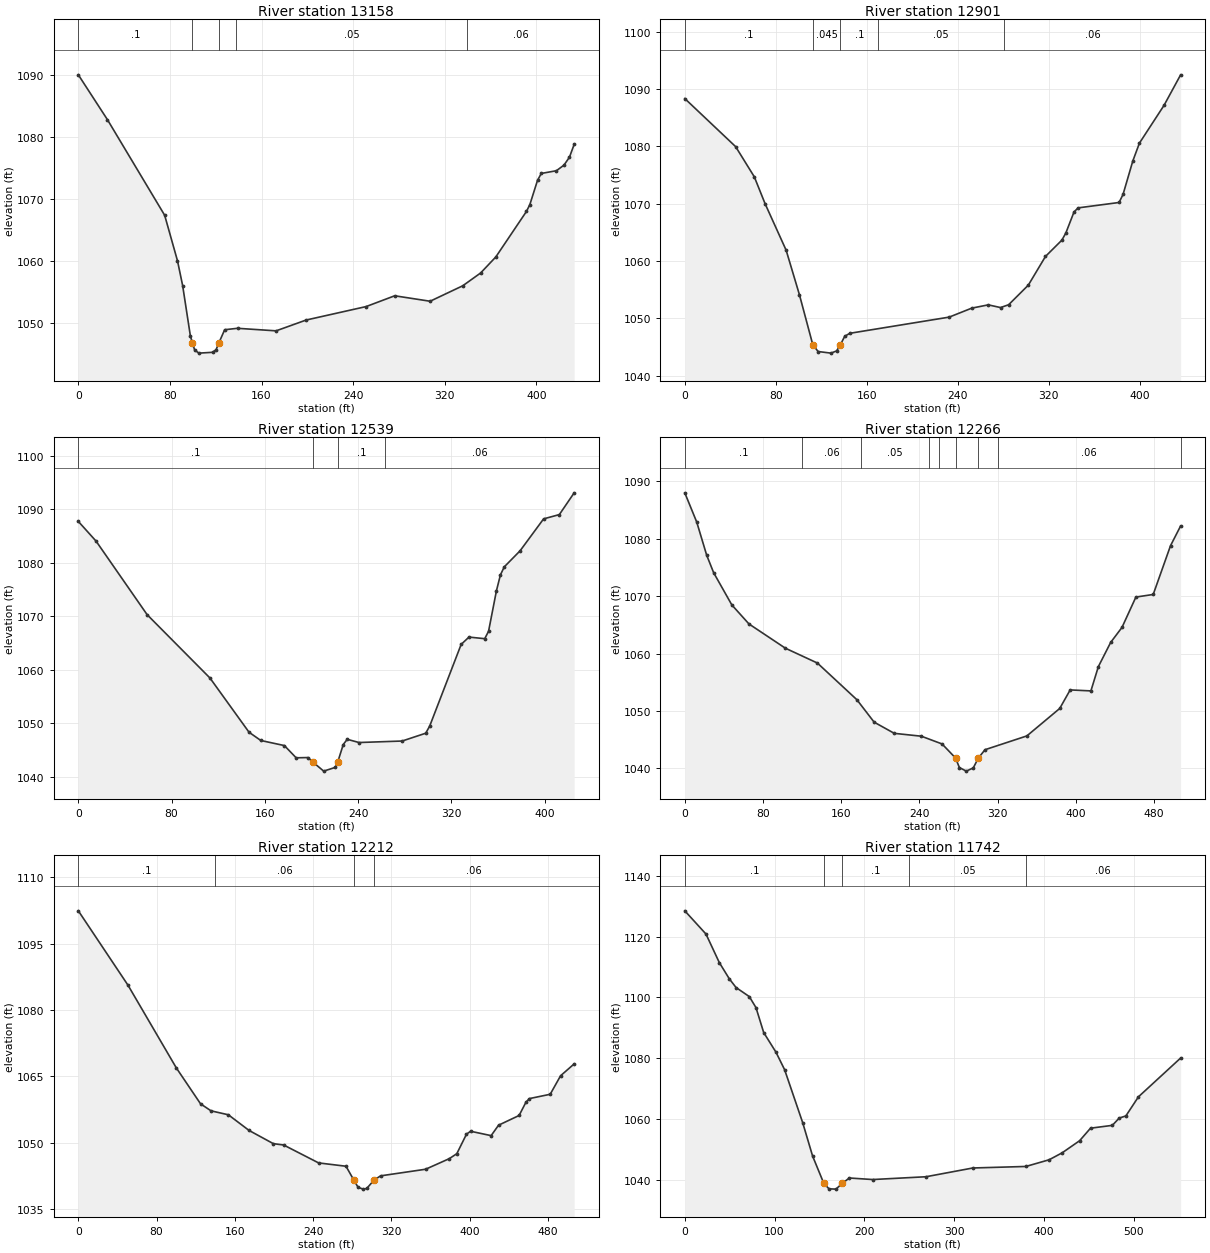
Type RM Length L Ch R = 1 ,13158   ,258.5,257.2,255
XS GIS Cut Line= 6
1668796.96153798492303.1522542341668839.13008881 492379.82073606
1668875.27470157492445.5364838941668923.46620623492533.158355887
 1668945.9845339492606.8202820671668958.04979848492699.518259401
#Sta/Elev= 30
       0 1090.06    25.4 1082.84    75.4 1067.43    86.6 1060.09    91.1  1056.1
    97.8 1048.05    99.61046.865   101.6 1045.72   105.3 1045.22   117.2 1045.35
   120.3 1045.77  122.721046.867   127.8 1048.99     139 1049.22   172.7 1048.81
   198.9 1050.55   251.3 1052.72   276.3 1054.46   307.2 1053.58   335.7 1056.07
   351.3 1058.13   364.6 1060.72   391.3 1068.04   394.3 1069.15     401 1073.06
   404.3 1074.17   417.5 1074.61   424.1 1075.51   428.9 1076.79     433 1078.85
#Mann= 5, -1 ,  0
       0     0.1       0    99.6   0.045       0  122.72     0.1       0
   137.5    0.05       0  339.53    0.06       0
Bank Sta=99.6,122.72
XS Rating Curve= 0 ,0
Exp/Cntr(USF)=0,0
Exp/Cntr=0.3,0.1

Type RM Length L Ch R = 1 ,12901   ,357.8,362.4,367.4
XS GIS Cut Line= 3
1668558.01402864492438.3893209651668693.67275622492612.687252285
1668781.30916703492809.055465146
#Sta/Elev= 30
       0 1088.35    44.7 1079.96    61.1  1074.7    70.6    1070    89.1 1061.89
   100.8 1054.11  112.541045.393   117.2 1044.22   128.5 1043.94   133.5 1044.33
  136.751045.392   140.6 1046.88   145.1  1047.4   232.4 1050.22   252.3 1051.79
   266.8 1052.36   277.6 1051.89   284.7 1052.38     302  1055.8   317.1 1060.81
   331.5 1063.65     335  1064.9   342.2 1068.58   345.8 1069.28   381.8 1070.22
   385.3 1071.64   393.9 1077.48   399.7 1080.58   421.3 1087.16   435.9 1092.49
#Mann= 5, -1 ,  0
       0     0.1       0  112.54   0.045       0  136.75     0.1       0
     170    0.05       0  280.87    0.06       0
Bank Sta=112.54,136.75
XS Rating Curve= 0 ,0
Exp/Cntr(USF)=0,0
Exp/Cntr=0.3,0.1

Type RM Length L Ch R = 1 ,12539   ,274.2,273.1,270.3
XS GIS Cut Line= 6
1668258.71296939492472.5105181161668278.99344064492557.851554793
1668294.67352738492631.2073792041668317.39821948 492728.59104271
1668334.44116438492801.6289543631668354.32465481492886.840070036
#Sta/Elev= 30
       0 1087.76    15.2 1084.08      59 1070.32   112.9 1058.47   146.4 1048.33
   156.5 1046.79   176.7 1045.84   186.8 1043.55   196.9  1043.6  200.881042.804
   210.4 1041.06   220.5 1041.77  222.521042.808   227.2 1046.04   230.6 1047.01
   240.7 1046.41   277.7 1046.69   297.9 1048.15   301.3 1049.48   328.3 1064.76
     335 1066.13   348.5 1065.83   351.8 1067.22   358.6 1074.84     362 1077.78
   365.3 1079.27   378.8 1082.26     399 1088.24   412.5 1089.04   425.2 1093.11
#Mann= 4, -1 ,  0
       0     0.1       0  200.88   0.045       0  222.52     0.1       0
  262.73    0.06       0
Bank Sta=200.88,222.52
XS Rating Curve= 0 ,0
Exp/Cntr(USF)=0,0
Exp/Cntr=0.3,0.1

Type RM Length L Ch R = 1 ,12266   ,54,54.1,54
XS GIS Cut Line= 2
 1667937.0227504492463.2188934151668127.22614307  492933.2368889
#Sta/Elev= 30
       0 1087.99    12.2  1082.9    22.4 1077.12    29.5 1074.08    48.1 1068.47
    65.6 1065.16   102.9 1060.93   135.6 1058.35     176 1051.96   193.6 1048.06
   214.2 1046.11   241.9 1045.61   263.1 1044.26  276.891041.809   280.8 1040.15
   287.9 1039.53     295 1040.09   300.21041.811     307 1043.26   349.8 1045.66
   383.4 1050.44   394.1 1053.67   415.3  1053.5   422.9 1057.72   435.5 1061.94
   447.1 1064.56   461.3 1069.84     479 1070.29   496.7 1078.78     507 1082.21
#Mann= 9, -1 ,  0
       0     0.1       0     120    0.06       0     180    0.05       0
     250    0.06       0     260    0.05       0  276.89   0.045       0
   300.2    0.05       0     320    0.06       0  507.04     0.1       0
Bank Sta=276.89,300.2
XS Rating Curve= 0 ,0
Exp/Cntr(USF)=0,0
Exp/Cntr=0.3,0.1

Type RM Length L Ch R = 1 ,12212   ,467.8,469.3,466.7
XS GIS Cut Line= 2
1667885.50336183492479.645917365 1668075.7067545492949.663912849
#Sta/Elev= 30
       0 1102.38    50.7 1085.61   100.3 1066.87     125 1058.79   135.7 1057.21
   153.4 1056.32   174.6 1052.78   199.4  1049.8     210 1049.49   245.7 1045.45
   273.7  1044.7   281.71041.577   286.1 1039.92   291.4 1039.53   294.9 1039.68
  302.391041.576   309.1 1042.53   355.1 1044.02   379.3 1046.41     387 1047.53
   396.9 1051.94   401.1  1052.6   422.1 1051.61   429.7 1053.97   450.7 1056.16
   457.7 1059.16   461.3 1059.98   482.5 1060.95   493.1 1065.13     507 1067.81
#Mann= 4, -1 ,  0
       0     0.1       0     140    0.06       0   281.7   0.045       0
  302.39    0.06       0
Bank Sta=281.7,302.39
XS Rating Curve= 0 ,0
Exp/Cntr(USF)=0,0
Exp/Cntr=0.3,0.1

Type RM Length L Ch R = 1 ,11742   ,249.7,248.3,249.3
XS GIS Cut Line= 2
1667555.25593025492594.3475914551667813.77778287493082.531293518
#Sta/Elev= 30
       0 1128.49    23.6 1120.86    38.5 1111.45    49.6 1106.14    57.1 1103.28
    71.9 1100.29    79.3 1096.68    87.9 1088.48   101.6 1082.01   111.2 1076.27
   131.3 1058.89   142.4 1047.87  154.911038.872   160.7 1037.11   168.4 1037.01
  175.341038.876   183.3 1040.67   209.3 1040.16   268.7 1041.08   320.9 1043.96
     380 1044.46   405.9 1046.66   420.5 1048.96   439.9 1052.93     452 1057.04
   476.3 1057.97     484 1060.37   491.4 1061.07   505.4 1067.35   552.4  1080.1
#Mann= 5, -1 ,  0
       0     0.1       0  154.91   0.045       0  175.34     0.1       0
     250    0.05       0     380    0.06       0
Bank Sta=154.91,175.34
XS Rating Curve= 0 ,0
Exp/Cntr(USF)=0,0
Exp/Cntr=0.3,0.1

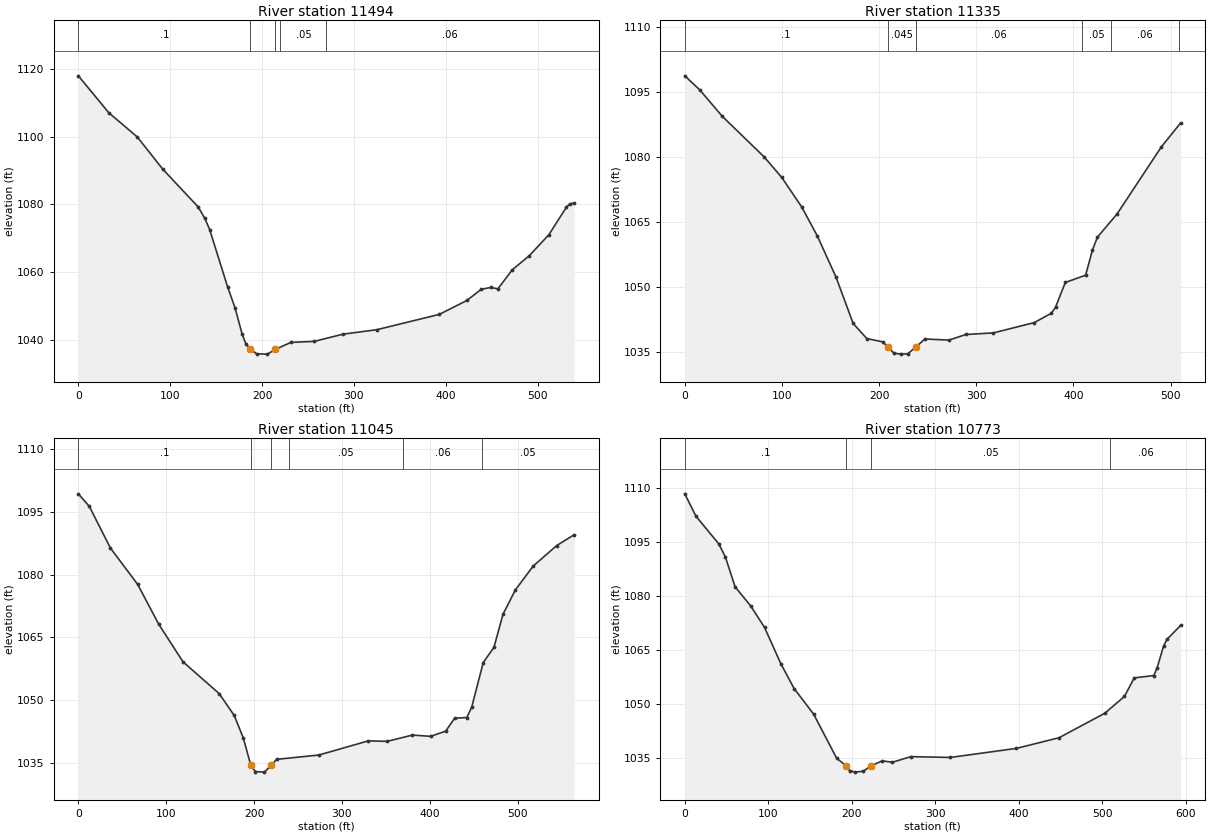
Type RM Length L Ch R = 1 ,11494   ,154.1,159.2,160.1
XS GIS Cut Line= 2
 1667342.7897695492741.6616423871667638.44066895493193.178706389
#Sta/Elev= 30
       0 1118.05    33.2 1107.11    64.2 1099.95      92 1090.39   130.6 1079.19
   137.7 1075.84     143  1072.5   162.6 1055.48   170.5 1049.43   178.3  1041.6
   182.2 1038.81  187.371037.079     194 1035.79   205.8 1035.67  214.551037.078
   231.3 1039.14   256.7 1039.44   288.1 1041.58   324.9  1042.9     393 1047.44
   422.9 1051.55   438.6 1054.86   448.9 1055.41   456.7    1055   472.4 1060.65
   490.8 1064.78   512.1 1070.99   531.2 1079.13   535.2  1080.2   539.7 1080.32
#Mann= 5, -1 ,  0
       0     0.1       0  187.37   0.045       0  214.55     0.1       0
     220    0.05       0     270    0.06       0
Bank Sta=187.37,214.55
XS Rating Curve= 0 ,0
Exp/Cntr(USF)=0,0
Exp/Cntr=0.3,0.1

Type RM Length L Ch R = 1 ,11335   ,275.9,289.5,294.9
XS GIS Cut Line= 3
1667210.98239144492810.6335501581667299.41724783492930.482037008
1667430.13107859493267.505162599
#Sta/Elev= 30
       0 1098.75    15.4 1095.51    38.5 1089.41    81.8 1079.99    99.7  1075.3
   120.2 1068.51   136.4 1061.76   155.7 1052.22   173.3 1041.53   187.4 1038.03
   204.1 1037.27   208.71036.091   215.5 1034.64   222.5 1034.44   229.6 1034.51
  237.841036.091   247.2 1037.94   271.8 1037.68   289.4 1038.98   317.6 1039.34
   359.8 1041.73   377.4  1043.9   381.6 1045.26   391.7    1051   412.6 1052.68
   419.6 1058.45   424.7 1061.45     445 1066.84   490.6 1082.34   510.4 1087.86
#Mann= 6, -1 ,  0
       0     0.1       0   208.7   0.045       0  237.84    0.06       0
  408.94    0.05       0  438.94    0.06       0  508.94    0.05       0
Bank Sta=208.7,237.84
XS Rating Curve= 0 ,0
Exp/Cntr(USF)=0,0
Exp/Cntr=0.3,0.1

Type RM Length L Ch R = 1 ,11045   ,268.3,272.9,275.1
XS GIS Cut Line= 2
1667132.99588122492796.8631807331666964.23971893493335.556894704
#Sta/Elev= 30
       0 1099.36    12.5 1096.35    36.6 1086.36    67.5  1077.7    91.6 1068.13
   119.1 1059.17   160.4 1051.53   177.5 1046.31   187.9 1040.88  196.331034.408
   201.6 1032.88   211.9 1032.75  219.71 1034.41   225.7 1035.81   273.8 1036.84
   330.1 1040.23   351.5 1040.11   380.4 1041.62     401 1041.32   418.2 1042.55
   428.5 1045.66   442.3 1045.82   447.9 1048.33     461 1058.98   473.2 1062.63
   483.5 1070.54   497.6 1076.36   517.9 1082.08   544.7 1086.99   564.5 1089.57
#Mann= 6, -1 ,  0
       0     0.1       0  196.33   0.045       0  219.71     0.1       0
     240    0.05       0     370    0.06       0     460    0.05       0
Bank Sta=196.33,219.71
XS Rating Curve= 0 ,0
Exp/Cntr(USF)=0,0
Exp/Cntr=0.3,0.1

Type RM Length L Ch R = 1 ,10773   ,335.3,332.2,326.1
XS GIS Cut Line= 2
1666950.72269397492689.4063540351666625.63623474493186.721520974
#Sta/Elev= 30
       0 1108.33    13.3 1102.16    40.7 1094.47    48.6 1090.84    60.3 1082.55
    78.9 1077.29    95.5 1071.32   115.2  1061.2     131 1054.36   154.4 1047.28
   181.9 1035.07  193.271032.953   197.5  1031.6   204.5 1031.21     214 1031.47
  222.971032.952   236.7 1034.34   248.5 1033.93   270.8  1035.5   318.3 1035.28
   397.4 1037.79   448.4 1040.74   503.3 1047.53   526.8 1052.19   538.5 1057.32
     562 1057.98     566 1060.16   573.8 1066.24   577.7 1067.97   594.1 1071.87
#Mann= 4, -1 ,  0
       0     0.1       0  193.27   0.045       0  222.97    0.05       0
     510    0.06       0
Bank Sta=193.27,222.97
XS Rating Curve= 0 ,0
Exp/Cntr(USF)=0,0
Exp/Cntr=0.3,0.1