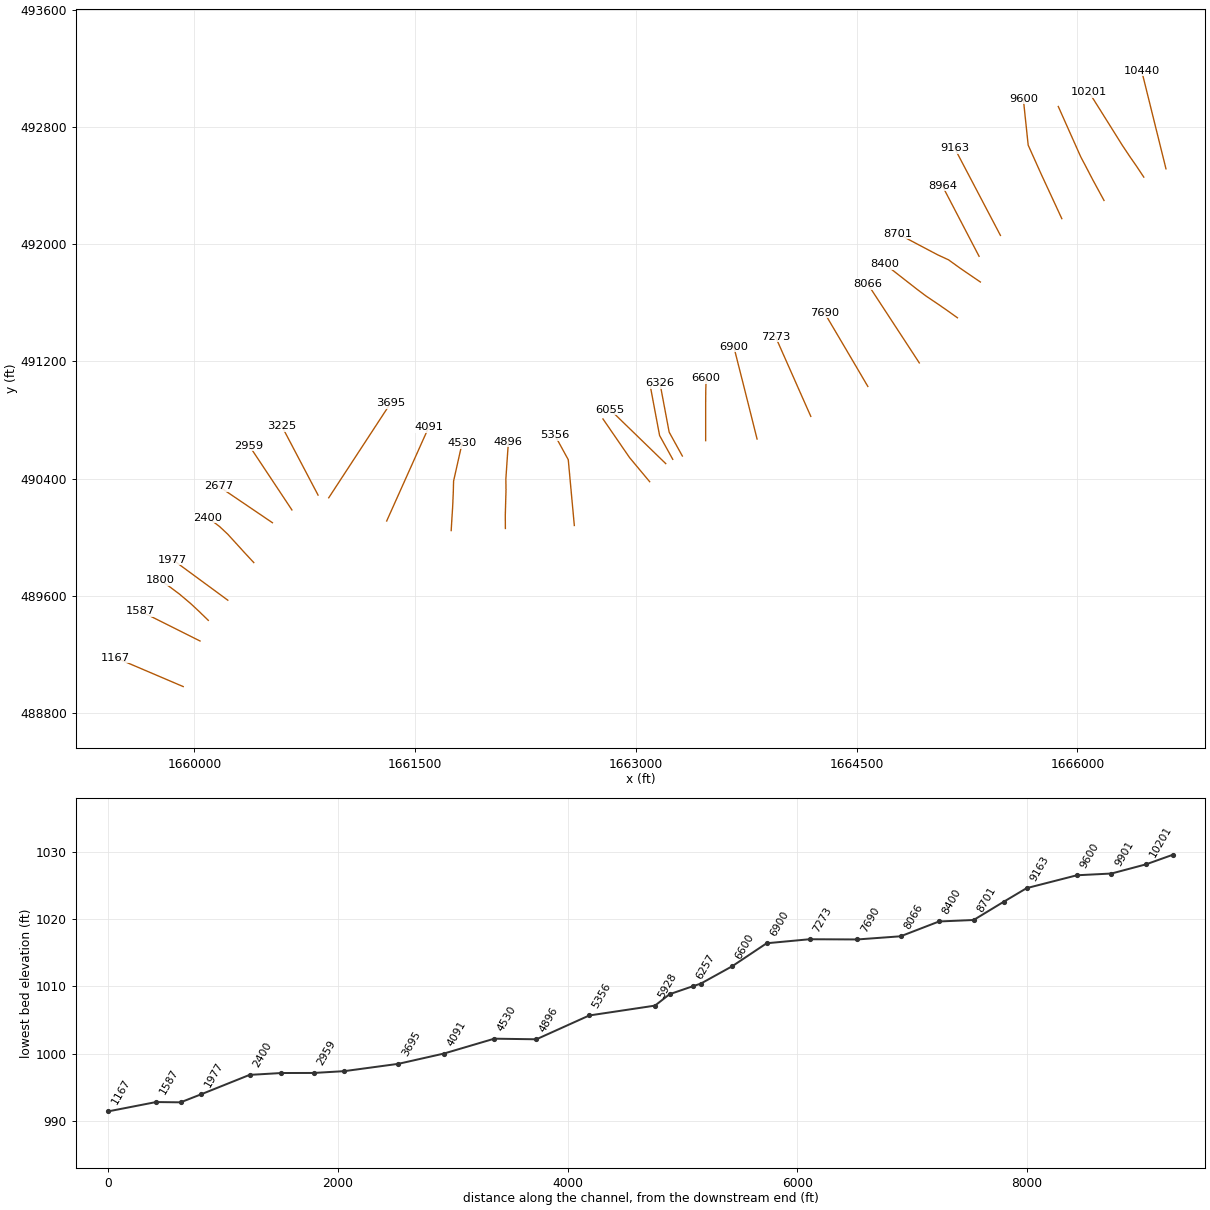
HEC-RAS study NFGraveCk.prj: NFGraveCk

--- NFGraveCk.g01 (geometry) --- (continued)

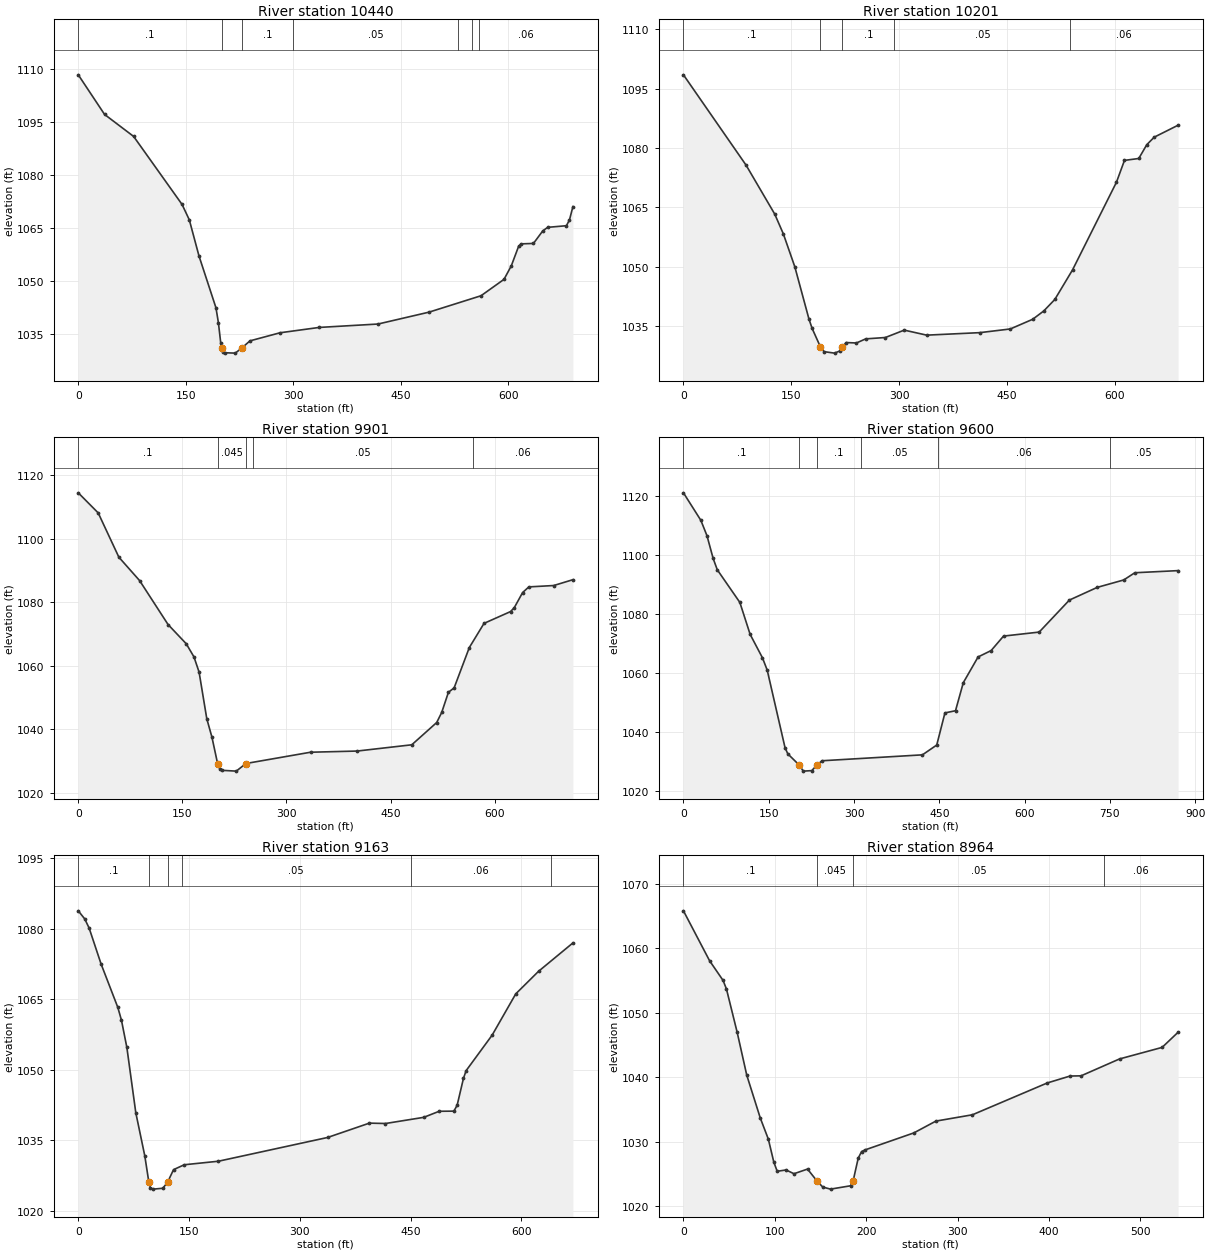
Type RM Length L Ch R = 1 ,10440   ,230.7,238.8,241.4
XS GIS Cut Line= 2
 1666602.0316232492513.9800446731666436.40112375493184.311051208
#Sta/Elev= 30
       0 1108.39    36.7 1097.19    77.3 1090.96   144.9 1071.72     155 1067.37
   168.5 1057.16   192.2  1042.5   195.6  1038.3   198.9  1032.5  200.731031.099
   202.3 1029.98   204.5 1029.78   219.2 1029.67  228.091031.095   239.7 1033.14
   281.7 1035.43   336.4 1036.94   418.4  1037.9   489.6 1041.26   562.2  1045.9
   594.3 1050.54   604.5 1054.37   614.6 1059.84     618 1060.57   635.4  1060.7
   648.4 1064.24   655.2 1065.25   681.4 1065.71   685.6  1067.3   690.5 1071.11
#Mann= 7, -1 ,  0
       0     0.1       0  200.73   0.045       0  228.09     0.1       0
     300    0.05       0     530    0.06       0     550    0.05       0
     560    0.06       0
Bank Sta=200.73,228.09
XS Rating Curve= 0 ,0
Exp/Cntr(USF)=0,0
Exp/Cntr=0.3,0.1

Type RM Length L Ch R = 1 ,10201   ,296.2,300.6,293.2
XS GIS Cut Line= 6
1666451.19747725492457.3241100911666402.68641943492530.590695843
1666359.77508792492592.5269236711666304.35262659492675.931940585
1666264.72934626492739.565999672 1666079.3567412493036.097657913
#Sta/Elev= 30
       0 1098.47    87.1 1075.67     127  1063.3     139 1058.29   154.9 1050.01
   174.7 1036.73     179 1034.44  190.411029.827   195.6 1028.58   210.2 1028.21
   218.1 1028.81   221.21029.827   226.4 1030.88   240.6 1030.77   253.5 1031.81
   280.8 1032.15   307.1 1034.02   338.3 1032.75   412.2 1033.38   454.6 1034.31
   485.7 1036.75   501.2 1038.86   516.5 1041.75   541.2 1049.23   602.3 1071.37
   613.4 1076.87   633.3 1077.35   644.4 1080.82   654.7 1082.72     688 1085.75
#Mann= 5, -1 ,  0
       0     0.1       0  190.41   0.045       0   221.2     0.1       0
  293.36    0.05       0  538.32    0.06       0
Bank Sta=190.41,221.2
XS Rating Curve= 0 ,0
Exp/Cntr(USF)=0,0
Exp/Cntr=0.3,0.1

Type RM Length L Ch R = 1 ,9901    ,301.1,300.9,298.8
XS GIS Cut Line= 6
1666180.96409383492298.0278407481666139.28898034492374.966007084
1666103.56792317492440.9127255831666057.52864517492529.702574253
1666022.30266576492596.6335427611665870.18269935492939.015930139
#Sta/Elev= 30
       0 1114.44    28.7 1108.12    58.5 1094.18    88.4 1086.81   129.4 1072.98
   155.6 1066.93   166.7  1062.8   174.1 1058.01   185.2 1043.32   192.6 1037.54
  200.751029.238   203.7 1027.59   207.4 1027.09   227.7 1026.84  241.631029.239
   334.7 1032.79   401.9 1033.16   480.6 1035.13   516.5 1042.14   523.7  1045.3
   533.4 1051.66   541.6 1053.04   563.5 1065.74   584.7 1073.35   622.9 1077.06
   628.2 1078.25   640.3 1083.05   649.3 1084.83   685.1 1085.26   712.8  1087.1
#Mann= 5, -1 ,  0
       0     0.1       0  200.75   0.045       0  241.63     0.1       0
   252.5    0.05       0  568.15    0.06       0
Bank Sta=200.75,241.63
XS Rating Curve= 0 ,0
Exp/Cntr(USF)=0,0
Exp/Cntr=0.3,0.1

Type RM Length L Ch R = 1 ,9600    ,436,437.4,437.4
XS GIS Cut Line= 6
1665894.11197726492174.1238890891665826.01303209492321.666244924
1665784.10629176492412.4619950951665752.67590842 492480.55831559
1665665.64157734492675.2967963861665632.35130939 492992.71171368
#Sta/Elev= 30
       0 1121.09    30.6 1111.76    41.4 1106.52    52.2 1098.83    59.5 1094.96
    99.2 1083.88   117.3 1073.02     139 1065.05   147.3  1060.9   178.7 1034.52
   183.6 1032.43  203.711028.627   210.8 1026.58   225.7 1026.75  234.611028.627
   243.7  1030.1   420.3 1032.11   445.5 1035.44   459.9 1046.35   478.5 1047.09
   492.2 1056.61   518.2 1065.35   541.2 1067.53     563 1072.44   625.7  1073.8
   678.8 1084.67   727.9 1088.99   774.4  1091.5   793.9 1093.95     870 1094.67
#Mann= 6, -1 ,  0
       0     0.1       0  203.71   0.045       0  234.61     0.1       0
   312.5    0.05       0   447.5    0.06       0   750.8    0.05       0
Bank Sta=203.71,234.61
XS Rating Curve= 0 ,0
Exp/Cntr(USF)=0,0
Exp/Cntr=0.3,0.1

Type RM Length L Ch R = 1 ,9163    ,196.6,198.4,196.3
XS GIS Cut Line= 2
1665477.05213203492059.6317212041665166.56699127492653.135031728
#Sta/Elev= 30
       0 1083.82     8.7 1082.11    14.7 1080.16    30.9 1072.51    53.6 1063.27
    58.5 1060.55    65.8 1054.77    77.9 1040.89    90.1 1031.71   95.611026.093
    97.6 1024.97   101.3 1024.66   114.4 1024.84  120.841026.095     129  1028.8
   143.5 1029.84   189.7 1030.59   337.6 1035.64   394.2 1038.69     416 1038.61
   467.8 1039.92   488.7 1041.21   508.6 1041.24     513 1042.48   521.6 1048.22
   525.2 1049.85   560.4 1057.39   592.4 1066.17   623.3 1070.97   669.8    1077
#Mann= 6, -1 ,  0
       0     0.1       0   95.61   0.045       0  120.84     0.1       0
     140    0.05       0     450    0.06       0     640    0.05       0
Bank Sta=95.61,120.84
XS Rating Curve= 0 ,0
Exp/Cntr(USF)=0,0
Exp/Cntr=0.3,0.1

Type RM Length L Ch R = 1 ,8964    ,247.5,262.8,268.8
XS GIS Cut Line= 2
  1665331.787523491917.277859996 1665082.3904342492397.768274406
#Sta/Elev= 30
       0  1065.8    28.6 1058.06    43.4    1055    47.1 1053.66    58.8 1046.96
    69.3 1040.31    84.1 1033.67    92.9  1030.4    98.9 1026.84   102.6 1025.41
   112.3 1025.61     121 1025.03   135.8 1025.75  146.351023.873   152.5 1022.96
     161 1022.64   182.9 1023.16  185.651023.871   191.3 1027.45     195 1028.46
   198.7 1028.72   252.2 1031.36   276.3 1033.19   316.3 1034.17   398.3 1039.11
   423.2 1040.18   435.2 1040.21   477.3 1042.83   523.9 1044.62   541.4 1046.97
#Mann= 4, -1 ,  0
       0     0.1       0  146.35   0.045       0  185.65    0.05       0
     460    0.06       0
Bank Sta=146.35,185.65
XS Rating Curve= 0 ,0
Exp/Cntr(USF)=0,0
Exp/Cntr=0.3,0.1

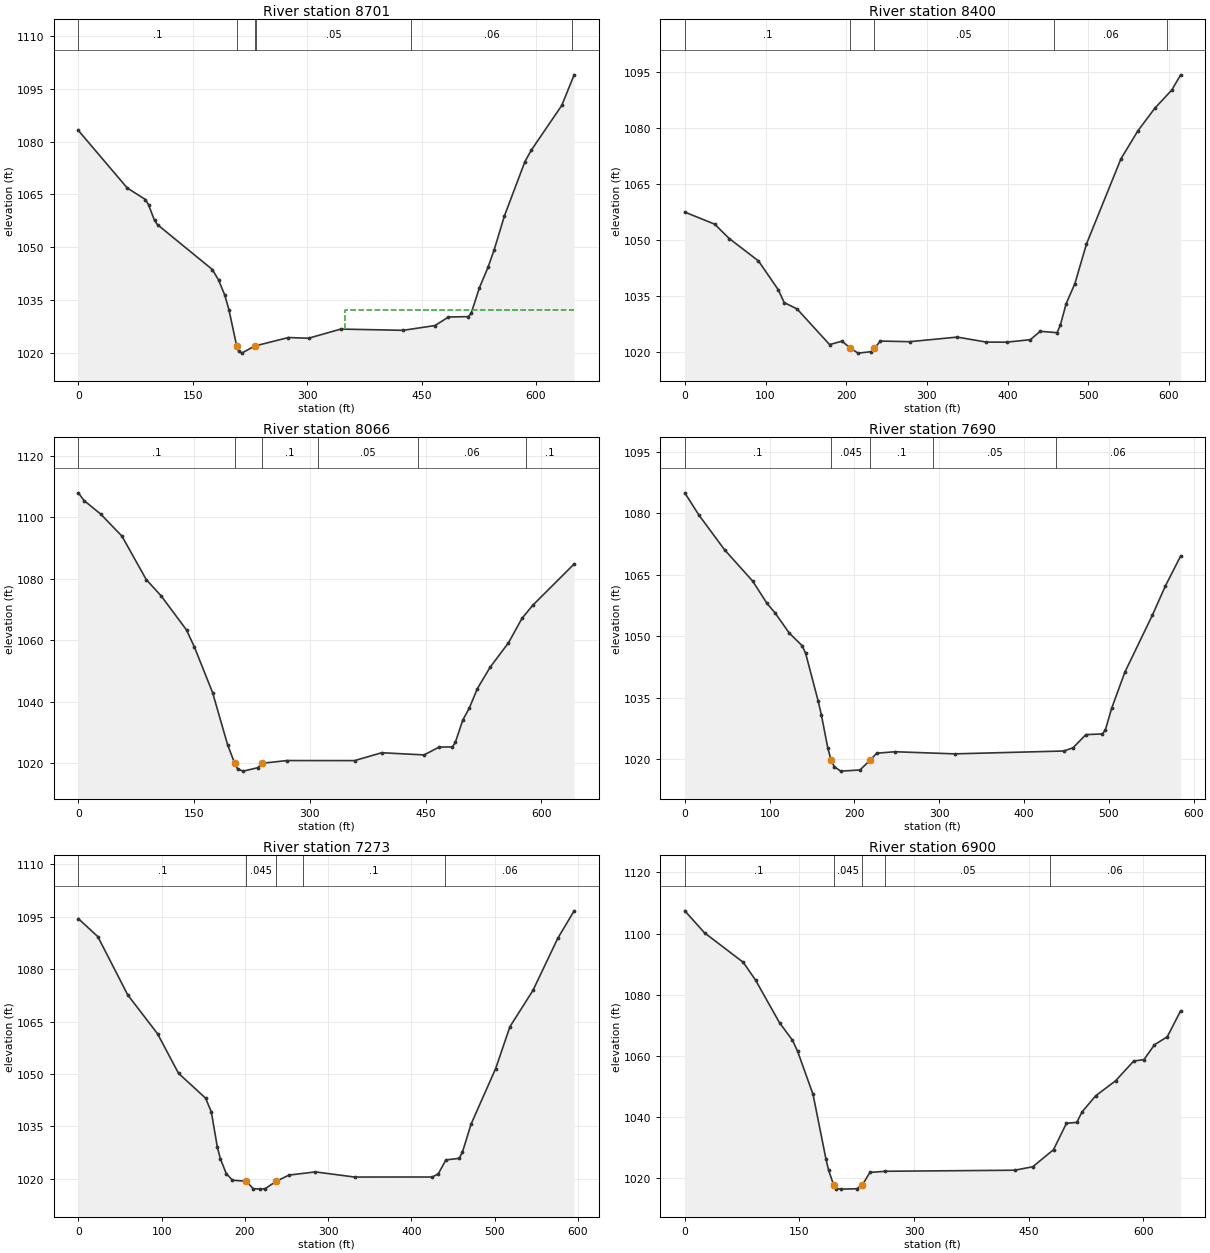
Type RM Length L Ch R = 1 ,8701    ,298.2,300.9,294
XS GIS Cut Line= 6
1665340.69805785491741.8898454161665268.48429151491791.300507754
1665206.58677751491833.6527852571665124.51870017491893.027010337
1665049.22029434491927.9708380851664781.24100496492070.057876274
#Sta/Elev= 30
       0 1083.17    64.1 1066.82      88 1063.54      92 1062.09    99.9 1057.59
   103.9 1056.38   175.7 1043.66   183.8 1040.71   191.9 1036.45   197.4 1032.29
  207.671021.899   210.6 1020.38   214.2 1019.91  231.341021.933   275.5 1024.34
   301.8 1024.14   344.2 1026.74   425.9 1026.39   467.6 1027.74   485.3 1030.17
   511.3 1030.28     515 1031.18   525.8 1038.43   537.3 1044.37   545.3 1049.31
   558.7 1058.91   585.5 1074.28   593.8 1077.53   633.8 1090.25   650.1 1098.96
#Mann= 6, -1 ,  0
       0     0.1       0  207.67   0.045       0  231.34     0.1       0
   232.5    0.05       0  436.81    0.06       0  646.81     0.1       0
#XS Ineff= 2 , 0
                          349.24         1032.26
Permanent Ineff=
       F       F
Bank Sta=207.67,231.34
XS Rating Curve= 0 ,0
Exp/Cntr(USF)=0,0
Exp/Cntr=0.3,0.1

Type RM Length L Ch R = 1 ,8400    ,337.6,334.6,321.8
XS GIS Cut Line= 6
1665184.81155859491497.8667114231665113.66898434491548.847908676
   1665052.06937491591.6565500941664969.27032301491647.735506177
1664909.40134826491692.9877122491664691.53100635491863.730399927
#Sta/Elev= 30
       0 1057.41    37.1 1054.18      55 1050.35    91.3 1044.35   115.8 1036.65
   123.2 1033.21   139.2 1031.49   179.4 1021.98   194.9 1022.89  204.891021.047
   214.7 1019.69   230.5 1020.07  235.031021.046   242.4 1022.92   278.5 1022.75
   337.6 1023.98   373.7 1022.64   398.8 1022.62   428.2 1023.29   440.4 1025.53
   461.3 1025.16   465.4 1027.22   472.6 1032.94   483.4  1038.3   497.7 1048.87
   540.4 1071.65   561.5 1079.17   582.4 1085.19   603.5 1090.08   614.4 1094.13
#Mann= 5, -1 ,  0
       0     0.1       0  204.89   0.045       0  235.03    0.05       0
  457.59    0.06       0  597.59     0.1       0
Bank Sta=204.89,235.03
XS Rating Curve= 0 ,0
Exp/Cntr(USF)=0,0
Exp/Cntr=0.3,0.1

Type RM Length L Ch R = 1 ,8066    ,374.6,375.7,373.2
XS GIS Cut Line= 2
1664925.84718151491189.9713298381664575.07848335491728.379806478
#Sta/Elev= 30
       0 1107.95     7.4 1105.45    29.1 1101.01    56.5 1093.88      88 1079.76
   107.4 1074.43   140.2 1063.37   150.5 1057.78     174 1043.01   193.5 1026.02
  202.641020.029   206.5 1018.14   213.7 1017.48   232.6 1018.59  237.941020.028
   270.6 1020.92     358  1020.9   393.2 1023.46   448.1 1022.75   467.6 1025.29
   484.9 1025.36   488.7 1026.89   498.2 1034.05   506.8 1038.02   517.1 1044.27
   533.7 1051.26   557.5  1059.2   575.1 1067.19     589 1071.41   642.6 1084.83
#Mann= 6, -1 ,  0
       0     0.1       0  202.64   0.045       0  237.94     0.1       0
     310    0.05       0     440    0.06       0     580     0.1       0
Bank Sta=202.64,237.94
XS Rating Curve= 0 ,0
Exp/Cntr(USF)=0,0
Exp/Cntr=0.3,0.1

Type RM Length L Ch R = 1 ,7690    ,418.4,416.9,412.8
XS GIS Cut Line= 6
1664575.93463849 491029.463839351664531.76970056491105.080486027
1664493.84097066491169.7831125241664443.26790907491256.051968855
1664405.33852299491320.7542672731664280.14563032491533.687797497
#Sta/Elev= 30
       0 1085.03    16.5 1079.64    46.9 1071.11    80.1 1063.44    96.9 1058.01
   106.4 1055.69   123.2 1050.75   138.2  1047.7   142.4 1045.86   157.2 1034.18
     161  1030.8   168.6 1022.66  172.411019.755   176.2 1018.11   183.8 1017.01
   206.6 1017.29  218.731019.756   226.3 1021.39   247.9 1021.75   318.3 1021.23
   446.9 1021.93   457.7 1022.71   472.9 1025.93   492.4  1026.1   495.8 1027.04
   503.4 1032.45     519 1041.26   551.4 1055.18   566.7  1062.3   584.6 1069.58
#Mann= 5, -1 ,  0
       0     0.1       0  172.41   0.045       0  218.73     0.1       0
  292.57    0.05       0  437.57    0.06       0
Bank Sta=172.41,218.73
XS Rating Curve= 0 ,0
Exp/Cntr(USF)=0,0
Exp/Cntr=0.3,0.1

Type RM Length L Ch R = 1 ,7273    ,374.7,373.3,367.6
XS GIS Cut Line= 2
1664188.26237059 490825.467137591663947.81597387491370.142368659
#Sta/Elev= 30
       0 1094.48    23.4 1089.34    59.3 1072.66    95.1 1061.53   120.3 1050.21
   152.8 1043.09   159.7 1039.15   166.9 1029.11   170.5 1025.78   177.6  1021.5
   185.1 1019.59  201.841019.294   209.9 1017.17   218.3 1017.04   224.3 1017.17
  237.811019.293   252.9 1021.06   284.6 1021.97   331.8  1020.5   425.1 1020.51
   432.3 1021.45   441.4  1025.4   457.4 1025.86   461.3 1027.68   471.7 1035.71
   501.1 1051.54   518.3 1063.56   545.9 1073.93   575.7 1088.85   595.4 1096.72
#Mann= 5, -1 ,  0
       0     0.1       0  201.84   0.045       0  237.81    0.05       0
     270     0.1       0     440    0.06       0
Bank Sta=201.84,237.81
XS Rating Curve= 0 ,0
Exp/Cntr(USF)=0,0
Exp/Cntr=0.3,0.1

Type RM Length L Ch R = 1 ,6900    ,304.3,300,294.9
XS GIS Cut Line= 6
   1663823.17419490670.9608849291663801.95146343490755.848182336
1663783.76055492490828.6085354981663759.50633834490925.622777179
1663741.31674217490998.3834584211663665.11476882491300.133340277
#Sta/Elev= 30
       0 1107.43    25.8 1100.24    76.5 1090.59    92.6 1084.77   123.9 1070.85
   140.8 1065.15   147.5 1061.57   167.8 1047.39   184.7 1026.26   188.1 1022.69
  194.691017.817   198.3 1016.59     205 1016.44   225.3 1016.57  232.361017.821
   242.2  1021.9   262.5 1022.28   431.7 1022.62   455.3 1023.76   482.4 1029.34
   499.3 1037.96   512.9 1038.26   519.6 1041.65   537.5 1046.94   563.6 1051.86
   587.3 1058.31   600.8  1058.8   614.5 1063.65   631.3 1066.27   648.7 1074.74
#Mann= 5, -1 ,  0
       0     0.1       0  194.69   0.045       0  232.36     0.1       0
   262.5    0.05       0   477.5    0.06       0
Bank Sta=194.69,232.36
XS Rating Curve= 0 ,0
Exp/Cntr(USF)=0,0
Exp/Cntr=0.3,0.1

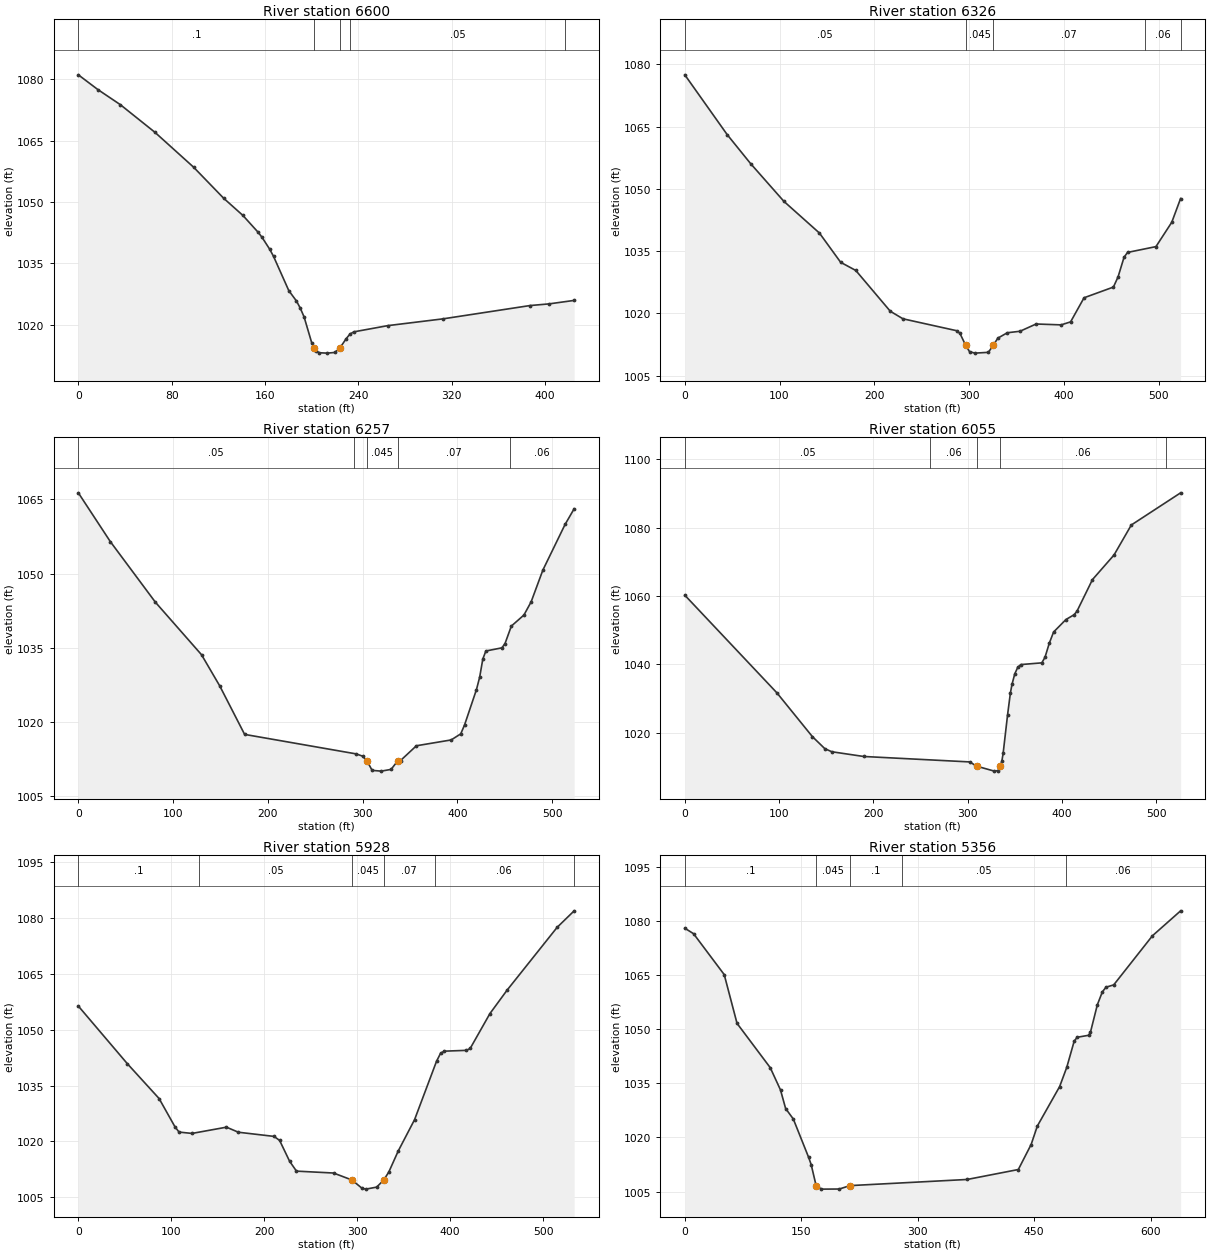
Type RM Length L Ch R = 1 ,6600    ,272.4,274.5,276.8
XS GIS Cut Line= 6
1663473.88223767490659.9454870081663473.88223767490747.445312008
1663473.88223767490822.4454900921663473.88223767490922.445618168
1663474.47180343490997.4454681721663476.82744175491084.945293173
#Sta/Elev= 30
       0 1081.11    16.7 1077.51      36 1073.81    65.6 1067.06    98.8 1058.51
   124.6  1050.9     141 1046.72   154.1 1042.59   157.4 1041.37     164 1038.45
   167.3  1036.7   180.4 1028.31     187 1025.75   190.2 1024.04   193.5 1021.88
   200.1 1015.49  202.311014.218   203.4 1013.59   206.6  1013.1   213.2 1013.01
   219.8 1013.17  224.071014.219   229.6 1016.55   232.9 1017.69   236.2 1018.22
   265.3 1019.74   312.4 1021.39   387.1 1024.65   403.5 1025.06     425 1025.91
#Mann= 5, -1 ,  0
       0     0.1       0  202.31   0.045       0  224.07     0.1       0
   232.5    0.05       0   417.5    0.06       0
Bank Sta=202.31,224.07
XS Rating Curve= 0 ,0
Exp/Cntr(USF)=0,0
Exp/Cntr=0.3,0.1

Type RM Length L Ch R = 1 ,6326    ,68.2,68.3,68.2
XS GIS Cut Line= 6
1663315.31672648490555.0907022921663225.73200852490717.915532157
1663211.92823035 490791.634216741663193.52242727490889.925686821
1663179.71832102490963.6446994841663163.61369444491049.649776816
#Sta/Elev= 30
       0 1077.48    44.7 1063.08    69.4  1056.1   104.6 1046.99   142.1 1039.35
   164.5  1032.3   180.5 1030.33   216.9  1020.5   230.3 1018.68     287 1015.81
   290.4 1015.17   296.51012.271   300.5 1010.77   306.2 1010.41   320.4  1010.6
  325.55 1012.27   330.4 1014.02   340.4 1015.32   353.8 1015.68   370.8 1017.43
   397.2 1017.22   407.2 1017.94   421.4 1023.75   452.4 1026.33   457.3 1028.78
   463.6  1033.5   467.3 1034.68   497.3 1036.08     514 1041.95   523.3 1047.67
#Mann= 5, -1 ,  0
       0    0.05       0   296.5   0.045       0  325.55    0.07       0
  485.84    0.06       0  523.34     0.1       0
Bank Sta=296.5,325.55
XS Rating Curve= 0 ,0
Exp/Cntr(USF)=0,0
Exp/Cntr=0.3,0.1

Type RM Length L Ch R = 1 ,6257    ,192.4,202,210.2
XS GIS Cut Line= 6
1663250.21205703490532.4082778161663160.62733908490695.233107681
 1663146.8235609490768.9517922641663128.41775782490867.243262345
1663114.61365157490940.9622750081663098.50902499 491026.96735234
#Sta/Elev= 30
       0 1066.33    33.7 1056.48    81.3 1044.21     130 1033.58   149.3 1027.25
   175.5 1017.46   293.4 1013.51   300.1 1013.05   304.71012.062   310.1 1010.18
   319.7 1010.03   330.1 1010.38  336.891012.063   340.1 1012.18   356.8 1015.16
   393.5 1016.34   403.6 1017.57   407.6 1019.36   420.2 1026.53   423.6 1029.06
   426.9 1032.71   430.1 1034.33     447 1034.97   450.3 1035.82     457 1039.37
   470.3 1041.61   477.9 1044.28   490.3 1050.71   513.7 1059.93   523.3 1063.11
#Mann= 5, -1 ,  0
       0    0.05       0  290.84    0.07       0   304.7   0.045       0
  336.89    0.07       0  455.84    0.06       0
Bank Sta=304.7,336.89
XS Rating Curve= 0 ,0
Exp/Cntr(USF)=0,0
Exp/Cntr=0.3,0.1

Type RM Length L Ch R = 1 ,6055    ,129.1,126.9,121.2
XS GIS Cut Line= 2
1663202.57580479490503.1560229131662825.82501845490869.886841527
#Sta/Elev= 30
       0 1060.24    97.7  1031.7   135.3 1018.92   148.5  1015.4   155.9  1014.5
   189.7 1013.12   302.1 1011.53  309.531010.291   328.2 1008.84   332.2    1009
  334.761010.288   336.2 1011.71   337.6 1014.06   342.3 1025.31   345.3 1031.71
     347  1034.2   349.9 1037.24   353.1 1039.18   356.4 1039.97   378.6 1040.47
     382 1042.11   386.5 1046.19   391.1 1049.48   404.2 1053.13   412.8 1054.52
   415.8 1055.51   432.3 1064.79   455.2 1071.99   473.5 1080.74   525.8 1090.14
#Mann= 5, -1 ,  0
       0    0.05       0     260    0.06       0  309.53   0.045       0
  334.76    0.06       0     510    0.05       0
Bank Sta=309.53,334.76
XS Rating Curve= 0 ,0
Exp/Cntr(USF)=0,0
Exp/Cntr=0.3,0.1

Type RM Length L Ch R = 1 ,5928    ,572,572.5,544.1
XS GIS Cut Line= 3
1663093.31274489490379.8107813011662956.96289816490543.818740299
1662775.97780227490807.925213216
#Sta/Elev= 30
       0 1056.37    52.8 1040.85    86.9  1031.5     104 1023.89   108.4 1022.48
   122.3 1022.12   159.4  1023.8   172.2 1022.44   210.6 1021.32   216.6 1020.23
   227.3 1014.65   234.7 1011.98   274.6 1011.47  294.411009.591   305.2 1007.38
   309.4 1007.14     321 1007.68   328.6 1009.59   334.1 1011.76   344.2 1017.39
   361.8 1025.83   385.4 1041.51   389.8 1043.69   393.8 1044.24   417.6 1044.46
   421.6 1044.96   442.9 1054.36   461.4 1060.67   515.2 1077.54   533.5 1081.98
#Mann= 6, -1 ,  0
       0     0.1       0     130    0.05       0  294.41   0.045       0
   328.6    0.07       0  383.28    0.06       0  533.28    0.05       0
Bank Sta=294.41,328.6
XS Rating Curve= 0 ,0
Exp/Cntr(USF)=0,0
Exp/Cntr=0.3,0.1

Type RM Length L Ch R = 1 ,5356    ,459.6,459.6,452.2
XS GIS Cut Line= 3
1662581.27137864490081.0767467511662540.03694357 490530.07392861
1662449.93206694490695.011668884
#Sta/Elev= 30
       0 1078.08    11.3 1076.55    50.8  1065.2    67.3 1051.67   110.1 1039.37
   123.3 1033.19   129.9 1028.04   139.8 1025.13   159.5 1014.51   162.8 1012.49
  169.191006.644     176 1005.67   199.1  1005.7  212.691006.642   363.8 1008.35
   429.7 1011.11   446.2 1018.05   454.2 1023.18   482.9 1034.12   492.1 1039.46
   501.6 1046.68   505.4 1047.81   520.3 1048.36   522.6 1049.18   531.5 1056.83
     538 1060.43   542.7 1061.71   552.6 1062.35   602.5 1075.98   638.8  1082.9
#Mann= 5, -1 ,  0
       0     0.1       0  169.19   0.045       0  212.69     0.1       0
     280    0.05       0  490.89    0.06       0
Bank Sta=169.19,212.69
XS Rating Curve= 0 ,0
Exp/Cntr(USF)=0,0
Exp/Cntr=0.3,0.1

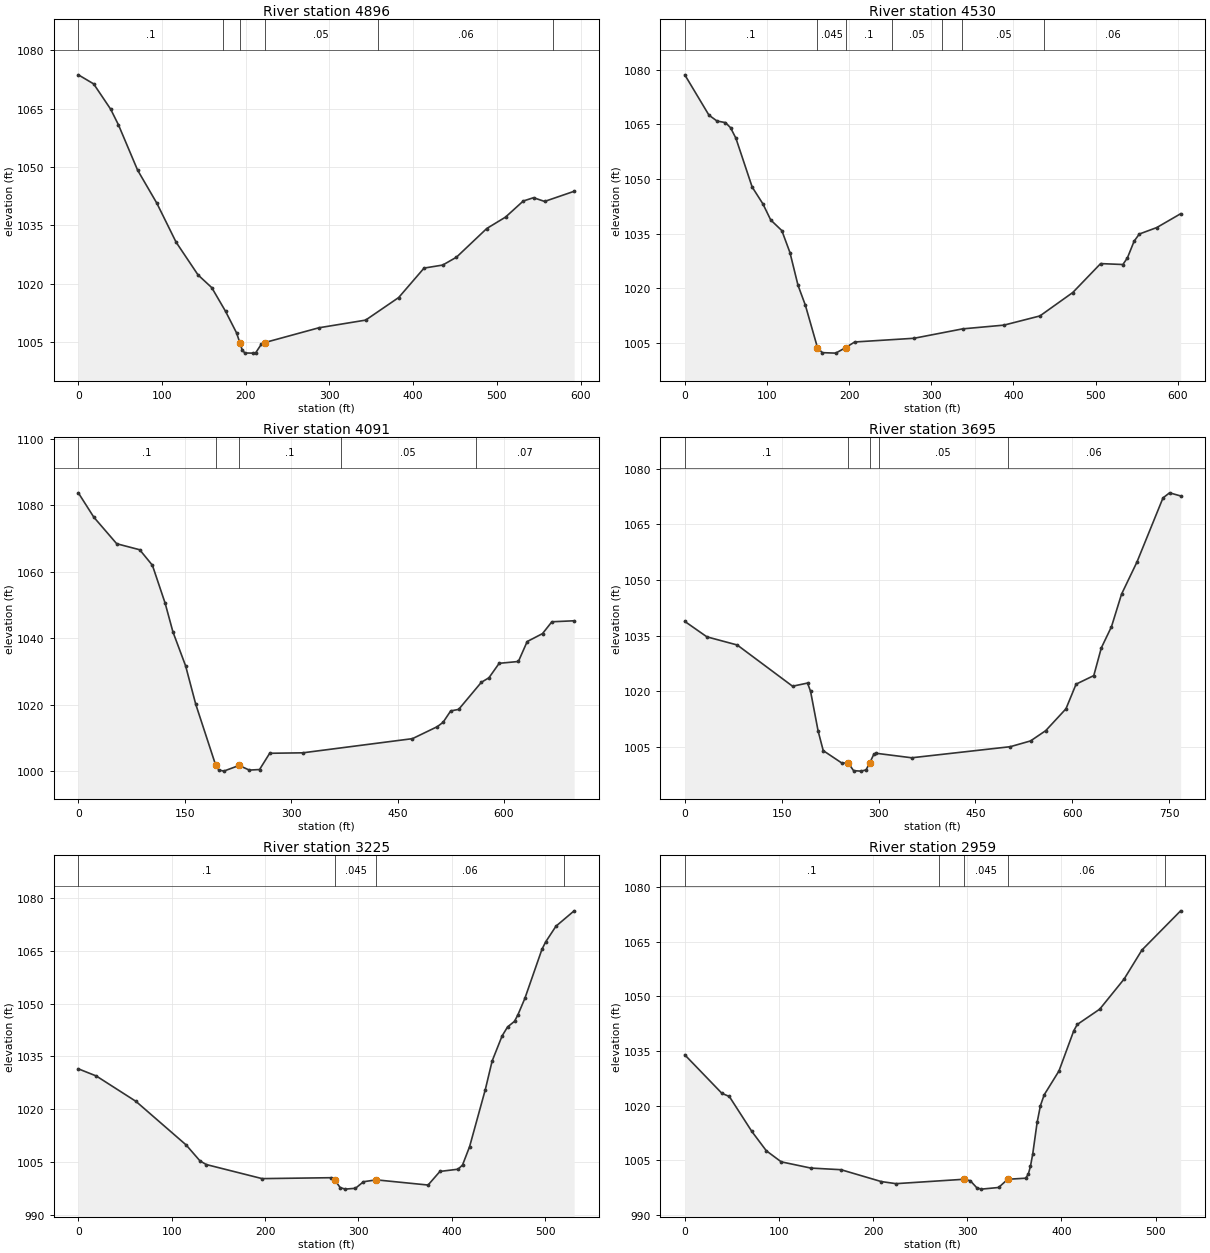
Type RM Length L Ch R = 1 ,4896    ,366.2,366.3,364
XS GIS Cut Line= 6
1662112.76386042490060.8443316691662112.14706376490148.395009595
1662114.23006484490223.3659882571662117.00696216490323.327730599
1662116.00466759490398.3843390071662133.26347338490652.444577827
#Sta/Elev= 30
       0 1073.69    18.3 1071.36    38.6 1064.86    47.9 1060.84    70.8 1049.18
    93.8 1040.67   116.8 1030.65     143 1022.23   159.4 1018.96   175.9 1012.86
     189 1007.33  192.871004.847   195.6 1003.03   198.8 1002.16   208.7 1002.12
     212 1002.25   218.5 1004.38  222.891004.846   287.4 1008.64   343.2 1010.61
   382.7 1016.42     413 1023.99   435.3 1024.77   451.7 1026.79   487.9 1034.17
   510.3  1037.1   531.5 1041.24   543.8 1042.09     557 1041.13   592.3 1043.74
#Mann= 6, -1 ,  0
       0     0.1       0  172.55    0.05       0  192.87   0.045       0
  222.89    0.05       0  357.62    0.06       0  567.62     0.1       0
Bank Sta=192.87,222.89
XS Rating Curve= 0 ,0
Exp/Cntr(USF)=0,0
Exp/Cntr=0.3,0.1

Type RM Length L Ch R = 1 ,4530    ,440.4,439.2,421.6
XS GIS Cut Line= 6
1661744.48520311490046.5917175651661749.64464162490134.091542566
1661754.44187613 490209.091720651661758.80899337490309.061008895
1661760.72434386490384.0244416391661818.76685148490643.308015365
#Sta/Elev= 30
       0 1078.62    29.4 1067.55    39.2 1065.94    49.5  1065.5    55.7  1064.1
    62.2 1061.22      82 1047.82    95.1 1043.18   104.6 1038.77   118.1 1035.86
     128 1029.83   137.8 1020.85   146.8 1015.35  161.531003.717   167.4 1002.34
   183.8 1002.21  195.711003.717   206.8 1005.27   279.1 1006.29   338.2 1008.87
   388.6  1009.9   432.3 1012.42   472.3 1018.85   506.2 1026.79   533.3 1026.54
   538.8 1028.35     547 1032.95   553.3 1034.91   574.5 1036.68   603.6 1040.48
#Mann= 7, -1 ,  0
       0     0.1       0  161.53   0.045       0  195.71     0.1       0
  252.81    0.05       0  312.87     0.1       0  337.86    0.05       0
  437.86    0.06       0
Bank Sta=161.53,195.71
XS Rating Curve= 0 ,0
Exp/Cntr(USF)=0,0
Exp/Cntr=0.3,0.1

Type RM Length L Ch R = 1 ,4091    ,394.9,395.7,388.6
XS GIS Cut Line= 2
1661306.13102359490111.7776553761661591.06978357490749.801630688
#Sta/Elev= 30
       0 1083.73    21.8 1076.41    54.1 1068.41    86.5  1066.6   104.4 1061.93
   122.4 1050.48   133.3  1041.9   151.2 1031.66   165.5  1020.1   193.71001.706
   197.9 1000.35     205  999.99   226.6  1001.7     241  1000.3   255.4 1000.47
   269.7 1005.36   316.4  1005.5   470.9 1009.76   505.9 1013.37   514.1 1014.69
   524.8 1018.11     536 1018.56     568 1026.72   578.7 1028.08   593.1 1032.43
   620.2 1032.98   632.6 1038.98   654.2 1041.37   667.4 1044.93   698.8 1045.23
#Mann= 5, -1 ,  0
       0     0.1       0   193.7   0.045       0   226.6     0.1       0
     370    0.05       0     560    0.07       0
Bank Sta=193.7,226.6
XS Rating Curve= 0 ,0
Exp/Cntr(USF)=0,0
Exp/Cntr=0.3,0.1

Type RM Length L Ch R = 1 ,3695    ,448.3,469.8,489
XS GIS Cut Line= 2
1660912.38243331490270.3157732581661331.60425273490913.683732215
#Sta/Elev= 30
       0 1038.84    34.2 1034.68    81.2 1032.48   166.9 1021.36   190.1 1022.21
   194.8 1019.97   206.5 1009.26   214.4 1003.99   242.7  1000.7  253.471000.585
   261.4  998.58   273.1  998.46   280.7  998.79  286.081000.583   292.7 1002.98
   296.6 1003.27   351.4 1002.06   504.1 1005.05   535.5 1006.61     559 1009.38
   590.3 1015.27     606 1021.92   633.4 1024.22   645.1 1031.71   660.8 1037.41
   676.4 1046.19   700.3 1054.87   740.6 1072.15   750.8 1073.52   767.9 1072.68
#Mann= 5, -1 ,  0
       0     0.1       0  253.47   0.045       0  286.08     0.1       0
     300    0.05       0     500    0.06       0
Bank Sta=253.47,286.08
XS Rating Curve= 0 ,0
Exp/Cntr(USF)=0,0
Exp/Cntr=0.3,0.1

Type RM Length L Ch R = 1 ,3225    ,258.3,265.8,261.6
XS GIS Cut Line= 2
1660839.67898293490288.5922805641660593.22233302  490759.1061014
#Sta/Elev= 30
       0 1031.49    19.2 1029.47    61.7 1022.27   115.5  1009.9   130.3 1005.39
     137 1004.35   196.9 1000.35     271 1000.61  274.731000.008   280.4  997.83
   285.8  997.37   296.9  997.61   305.5  999.47   319.2    1000   374.7  998.53
   387.4 1002.39   406.8 1003.02   411.6 1004.21   419.2 1009.44     436 1025.59
   443.3 1033.69     454 1040.83   459.9 1043.39   467.3 1044.97     471 1046.85
   478.4 1051.48   496.7  1065.4   500.6 1067.46   511.7 1071.95   531.2 1076.31
#Mann= 4, -1 ,  0
       0     0.1       0  274.73   0.045       0   319.2    0.06       0
     520     0.1       0
Bank Sta=274.73,319.2
XS Rating Curve= 0 ,0
Exp/Cntr(USF)=0,0
Exp/Cntr=0.3,0.1

Type RM Length L Ch R = 1 ,2959    ,268.2,282.7,285.7
XS GIS Cut Line= 2
1660661.98921879490187.3767790461660371.44989127490626.525965361
#Sta/Elev= 30
       0 1033.95    39.4 1023.39    47.3 1022.52    71.2 1012.93    86.6 1007.62
   102.4 1004.59   133.8 1002.88   165.9 1002.43   208.6  999.18   224.3   998.6
   296.1   999.8   303.2  999.41   310.3  997.43     315   997.1   333.3  997.55
  342.93 999.803     362  1000.1   364.8 1001.19   367.1 1003.35   369.5  1006.7
   374.2 1015.41   377.7 1020.01   381.7 1022.98   397.4 1029.53   413.1 1040.55
   416.8 1042.28   440.7 1046.49   466.6 1054.76   485.5 1062.71   526.6 1073.47
#Mann= 5, -1 ,  0
       0     0.1       0     270    0.06       0   296.1   0.045       0
  342.93    0.06       0     510     0.1       0
Bank Sta=296.1,342.93
XS Rating Curve= 0 ,0
Exp/Cntr(USF)=0,0
Exp/Cntr=0.3,0.1

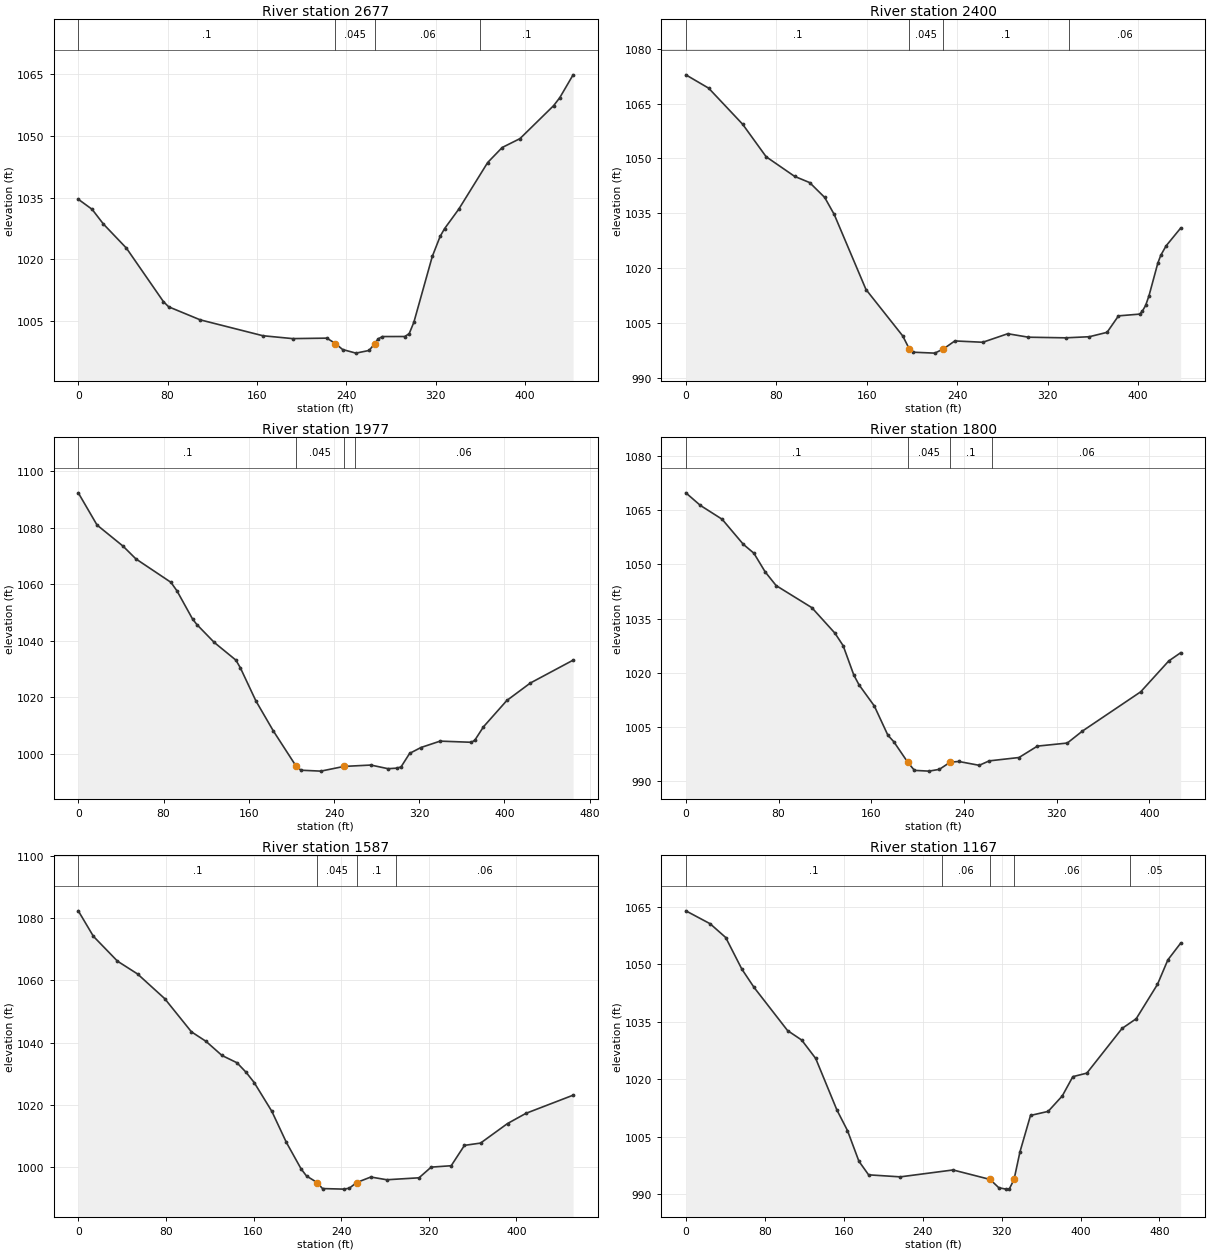
Type RM Length L Ch R = 1 ,2677    ,276.7,276.7,271.6
XS GIS Cut Line= 2
1660529.48885857490100.1980219621660163.11959087490349.433007209
#Sta/Elev= 30
       0 1034.59    12.4 1032.13    22.5 1028.55    43.1 1022.68    76.2 1009.66
    80.9 1008.38   109.2  1005.2   165.3 1001.33   191.9 1000.63   222.6 1000.74
   230.3999.4219   236.7  997.97   248.6  997.09   260.4  997.74   265.5  999.42
   268.5 1000.56   272.4 1001.13   292.3 1001.14   296.3 1001.82   300.5 1004.61
     317 1020.65     324 1025.52     328 1027.43   340.7 1032.17   366.6 1043.54
   379.6  1047.2   395.5 1049.36   425.7 1057.41   431.2 1059.36   443.1 1064.91
#Mann= 4, -1 ,  0
       0     0.1       0   230.3   0.045       0   265.5    0.06       0
     360     0.1       0
Bank Sta=230.3,265.5
XS Rating Curve= 0 ,0
Exp/Cntr(USF)=0,0
Exp/Cntr=0.3,0.1

Type RM Length L Ch R = 1 ,2400    ,415,423.5,418.2
XS GIS Cut Line= 6
1660402.99697526489828.2056806681660343.35929926489892.346300423
1660293.04673584489947.9669240861660225.77816959490021.960214421
1660170.38720426490074.0772361761660091.73184976490134.095488846
#Sta/Elev= 30
       0 1072.84    20.2 1069.19    50.2 1059.35      71 1050.46    96.2  1045.1
   109.5  1043.4   122.8 1039.34   131.2  1034.7   159.3 1014.19   191.8 1001.51
   197.6997.9747   201.1  997.06   220.2  996.81  227.84997.9744   237.9 1000.14
   262.6  999.78   284.7 1002.11     303 1001.16   335.8 1000.99   356.8 1001.29
   372.5 1002.49   382.6 1006.99   401.3 1007.47   403.6 1008.23   406.6 1009.83
   409.6 1012.51   417.4 1021.41     420 1023.54   424.7 1026.11   437.6 1030.98
#Mann= 4, -1 ,  0
       0     0.1       0   197.6   0.045       0  227.84     0.1       0
  338.64    0.06       0
Bank Sta=197.6,227.84
XS Rating Curve= 0 ,0
Exp/Cntr(USF)=0,0
Exp/Cntr=0.3,0.1

Type RM Length L Ch R = 1 ,1977    ,173.6,176.5,170.6
XS GIS Cut Line= 2
1660226.50654744489571.4933623221659852.74169972489847.034244906
#Sta/Elev= 30
       0 1092.31    17.6 1080.92      42 1073.46    54.1 1068.94    86.9 1060.68
    92.6 1057.66   107.2 1047.72   111.3 1045.73   127.6 1039.41   147.9 1033.16
   152.1 1030.45   166.7 1018.73   183.1 1008.09  204.59995.5668   209.1  994.22
   227.7   993.9  249.26995.5609   274.6  996.05   290.7  994.76   298.8  994.95
   302.9  995.38     311 1000.18   321.6 1002.25   339.6 1004.51     369  1004.1
   372.2 1004.86   380.3 1009.58   402.2 1018.88   424.3 1025.06   464.4 1033.14
#Mann= 4, -1 ,  0
       0     0.1       0  204.59   0.045       0  249.26     0.1       0
     260    0.06       0
Bank Sta=204.59,249.26
XS Rating Curve= 0 ,0
Exp/Cntr(USF)=0,0
Exp/Cntr=0.3,0.1

Type RM Length L Ch R = 1 ,1800    ,207.6,213.4,216.5
XS GIS Cut Line= 6
1660093.70723951489434.2786470061660030.13682859489496.147617757
1659975.06902534489547.6776984191659898.87396775489612.441676512
 1659838.8061745489657.5685547591659767.66720918489708.810250178
#Sta/Elev= 30
       0 1069.82    12.5 1066.34    31.3  1062.5    49.6 1055.55    58.7 1053.09
    68.5 1047.89    77.9 1044.12   108.7 1038.01   128.6 1030.95   135.7 1027.48
   144.9 1019.35   149.4 1016.63   162.6 1010.77   174.3 1002.67   179.4 1000.87
  191.35995.2237   197.2  992.93   209.7  992.72   218.7  993.21  228.16995.2162
   235.5  995.39   253.1  994.33   261.7  995.56   287.4  996.49   303.3  999.65
   329.1  1000.5   342.1 1003.81   392.4 1014.69   416.6 1023.24   426.9 1025.52
#Mann= 4, -1 ,  0
       0     0.1       0  191.35   0.045       0  228.16     0.1       0
  264.12    0.06       0
Bank Sta=191.35,228.16
XS Rating Curve= 0 ,0
Exp/Cntr(USF)=0,0
Exp/Cntr=0.3,0.1

Type RM Length L Ch R = 1 ,1587    ,412.6,419.4,413.3
XS GIS Cut Line= 2
1660037.66129115489293.3191545781659633.92141367489496.082985342
#Sta/Elev= 30
       0 1082.44    13.8 1074.23    35.8 1066.22    54.1  1062.1    78.9 1054.15
   103.3 1043.45   116.6 1040.39   131.2 1035.83   144.9 1033.48   153.3 1030.38
   160.6 1027.11   176.7 1017.85     190 1007.82   203.5  999.25   208.4  996.99
  218.13994.8782     223  992.94   242.6  992.76   247.5  993.07  254.13994.8783
   267.1  996.66   281.7  995.78   311.1  996.41   322.2  999.85   340.5  1000.3
   352.6 1006.86   367.3  1007.6   391.9 1013.89   408.8 1017.19   451.8 1023.03
#Mann= 4, -1 ,  0
       0     0.1       0  218.13   0.045       0  254.13     0.1       0
     290    0.06       0
Bank Sta=218.13,254.13
XS Rating Curve= 0 ,0
Exp/Cntr(USF)=0,0
Exp/Cntr=0.3,0.1

Type RM Length L Ch R = 1 ,1167    ,308,316.6,316.9
XS GIS Cut Line= 2
1659923.27987702488982.4382584661659462.23616098489179.825773047
#Sta/Elev= 30
       0 1063.96    24.6 1060.59    40.4    1057    56.7 1048.78    69.1 1043.99
   103.1 1032.72   117.4 1030.25   131.6 1025.45   153.1    1012   163.8 1006.64
   175.4  998.64   185.2  995.09   217.3  994.56   270.8  996.36  308.31 993.889
   317.2  991.72   324.4  991.36   327.9  991.45  332.63993.8861   338.6 1001.06
   349.3 1010.58   367.2 1011.64   381.5 1015.67   392.2  1020.7   406.4 1021.62
   442.1 1033.28   456.4  1035.8     478 1044.78   488.5 1051.16   501.5 1055.53
#Mann= 5, -1 ,  0
       0     0.1       0     260    0.06       0  308.31   0.045       0
  332.63    0.06       0     450    0.05       0
Bank Sta=308.31,332.63
XS Rating Curve= 0 ,0
Exp/Cntr(USF)=0,0
Exp/Cntr=0.3,0.1