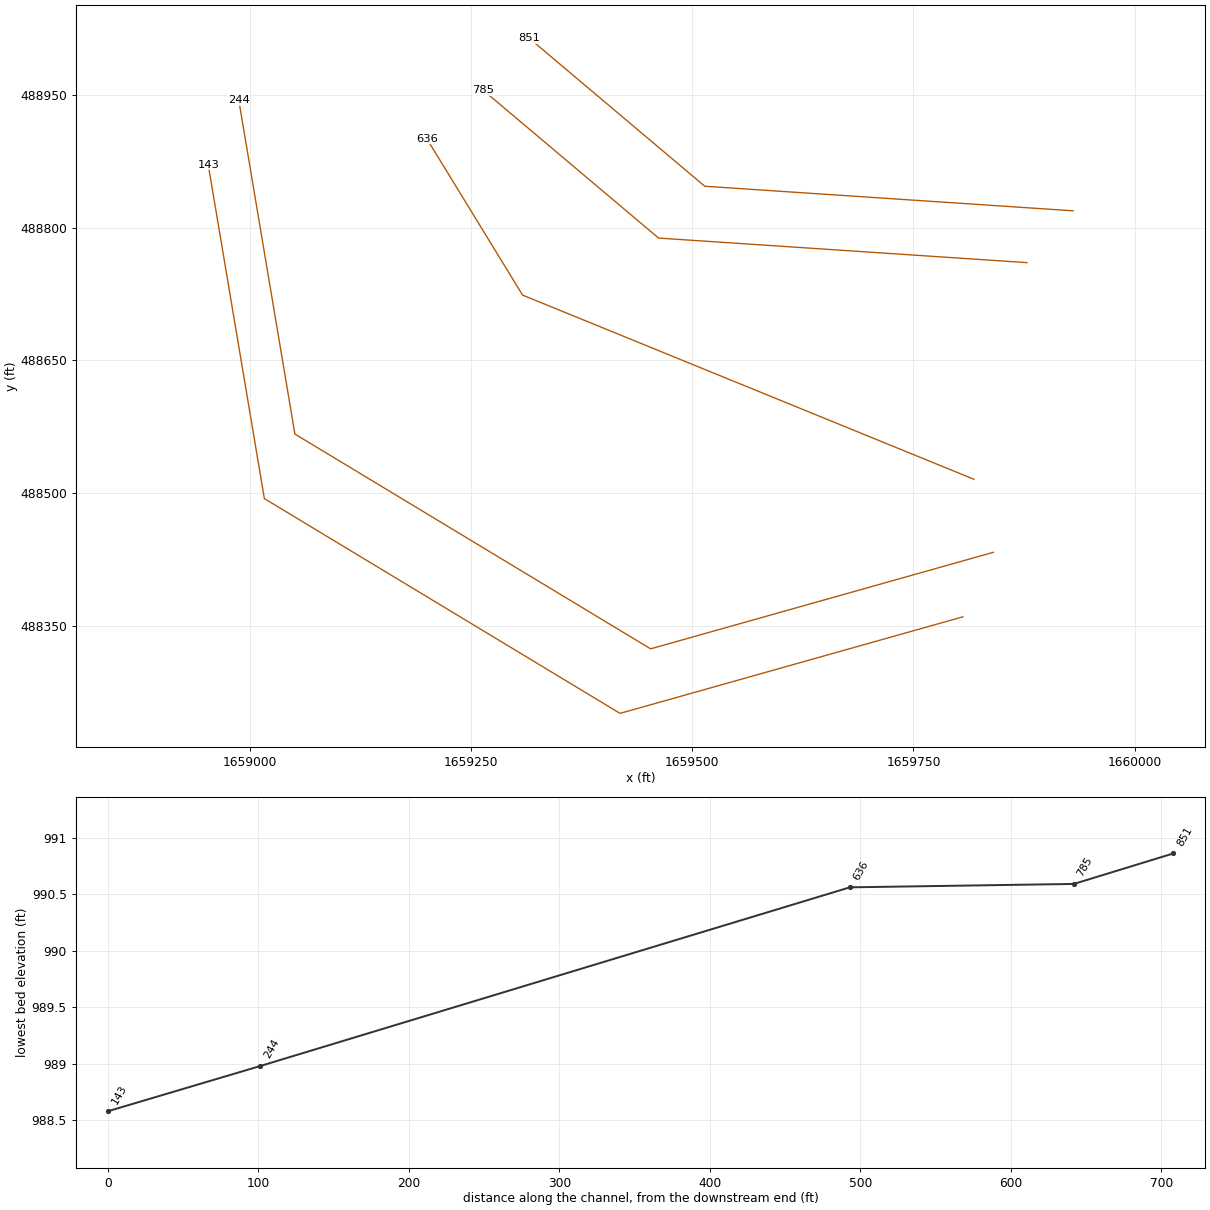
HEC-RAS study NFGraveCk.prj: NFGraveCk

--- NFGraveCk.g01 (geometry) --- (continued)

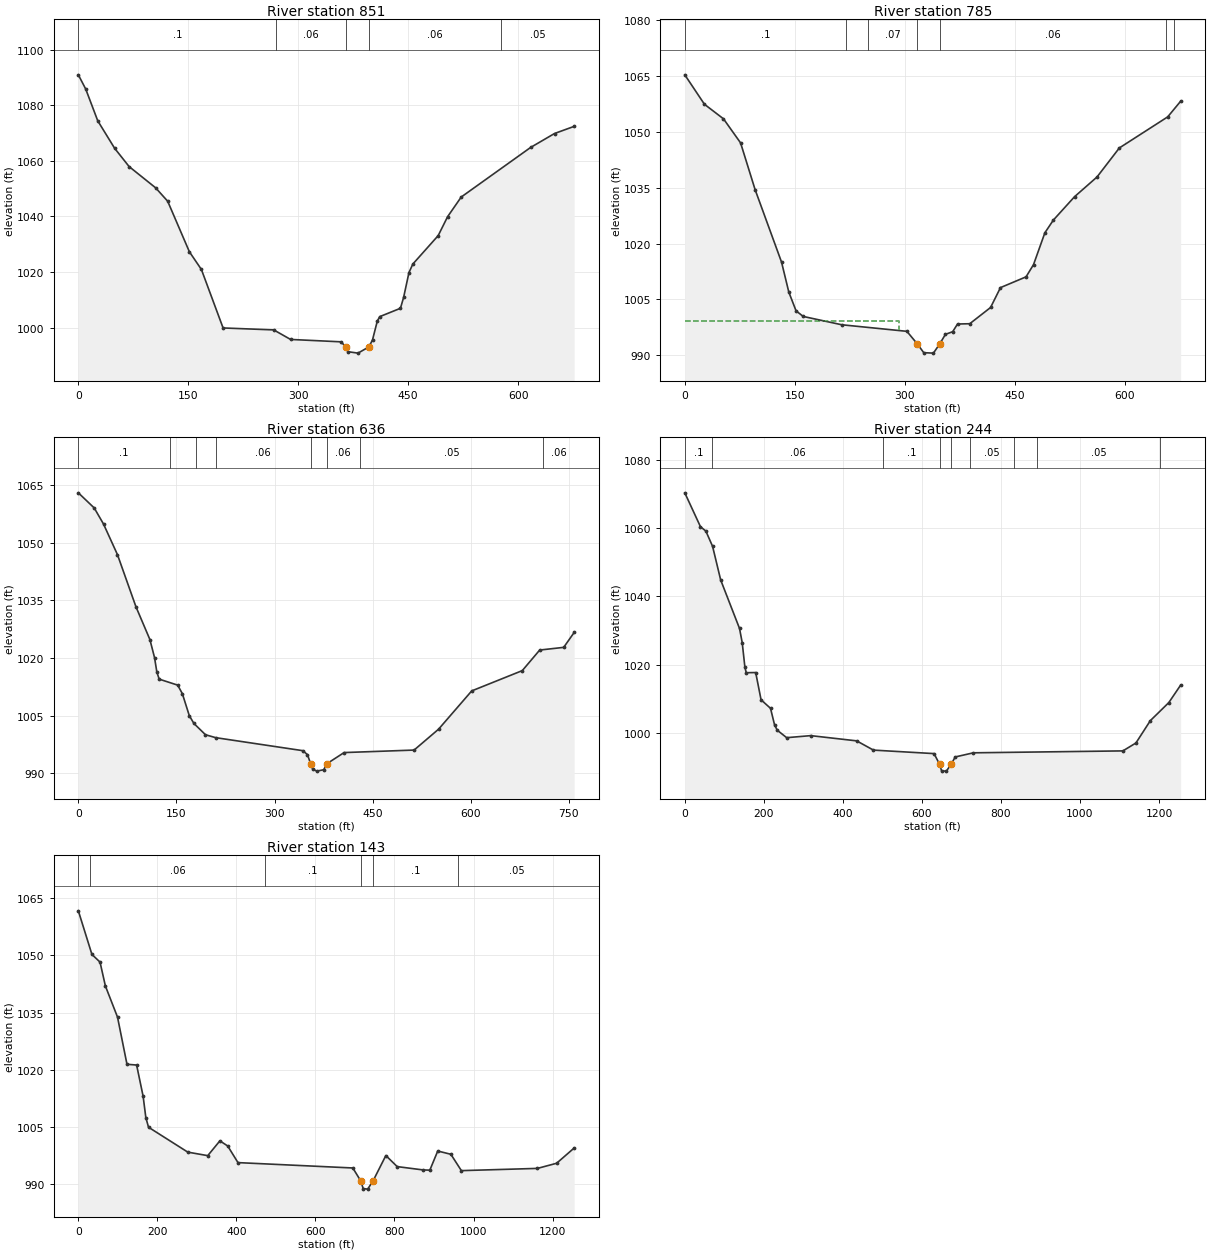
Type RM Length L Ch R = 1 ,851     ,64.5,66.2,64.6
XS GIS Cut Line= 3
1659930.43967089488818.9094201961659514.20534774488846.667838746
1659315.94833897489013.810461668
#Sta/Elev= 30
       0 1090.92    10.1 1085.79    26.5 1074.38    49.5 1064.52    69.3 1057.93
   105.4 1050.31   121.9 1045.48   151.5 1027.31   167.9 1020.94   197.5  999.91
   266.6  999.21   289.6  995.78   358.6  994.92  364.67993.1315   368.5  991.35
   381.6  990.86  396.63993.1309   401.4  995.65   407.9 1002.37   411.2 1003.98
   439.5 1006.98   443.8 1010.88   451.1 1019.82   456.4 1022.89     491 1033.12
   503.8  1039.9   522.4 1046.98   617.1 1064.81   649.7 1069.82   676.5 1072.39
#Mann= 5, -1 ,  0
       0     0.1       0     270    0.06       0  364.67   0.045       0
  396.63    0.06       0  577.16    0.05       0
Bank Sta=364.67,396.63
XS Rating Curve= 0 ,0
Exp/Cntr(USF)=0,0
Exp/Cntr=0.3,0.1

Type RM Length L Ch R = 1 ,785     ,151.4,148.8,141.2
XS GIS Cut Line= 3
1659878.23083079488760.3506154791659461.99650763488788.109034029
1659263.73949886488955.251656951
#Sta/Elev= 30
       0 1065.27    26.8 1057.37    52.8 1053.46    76.1 1047.01    95.9 1034.48
     132 1015.01   141.9 1006.98   151.8 1001.94   161.6 1000.43   214.2   998.2
     303  996.44  317.48993.0078     326  990.71   339.2  990.59  347.65993.0083
   355.6  995.63   365.5  996.34   372.1   998.4   388.8  998.48   417.2 1002.84
   430.7 1008.17   465.6 1011.06   475.8 1014.34   491.3 1022.89   502.9  1026.3
   531.8 1032.57   562.4 1037.85   592.9 1045.65   658.9 1053.99   676.5 1058.18
#Mann= 7, -1 ,  0
       0     0.1       0     220    0.06       0     250    0.07       0
  317.48   0.045       0  347.65    0.06       0  657.16    0.05       0
  667.16    0.06       0
#XS Ineff= 2 , 0
          291.62  999.16
Permanent Ineff=
       F       F
Bank Sta=317.48,347.65
XS Rating Curve= 0 ,0
Exp/Cntr(USF)=0,0
Exp/Cntr=0.3,0.1

Type RM Length L Ch R = 1 ,636     ,387.5,391.7,385.8
XS GIS Cut Line= 3
1659818.24800923 488515.597989211659308.34013985488723.663991735
1659200.08620942488900.395368105
#Sta/Elev= 30
       0 1062.99    24.3 1059.05    38.5 1054.87    59.8 1046.91    88.1 1033.33
   109.4 1024.81   116.5 1020.11     120 1016.37   123.6  1014.5   151.9 1012.94
     159 1010.73   169.6 1005.02   176.7 1002.96   194.4 1000.03     210  999.27
   343.3  995.88   350.3  994.84  355.11992.4993   358.5  991.06   364.5  990.56
   375.1  990.92  380.08   992.5   406.3  995.39   513.3  996.04   550.7 1001.47
   601.4 1011.44   678.7 1016.72   705.3 1022.07     742 1022.77     758 1026.65
#Mann= 8, -1 ,  0
       0     0.1       0     140    0.06       0     180     0.1       0
     210    0.06       0  355.11   0.045       0  380.08    0.06       0
     430    0.05       0  710.72    0.06       0
Bank Sta=355.11,380.08
XS Rating Curve= 0 ,0
Exp/Cntr(USF)=0,0
Exp/Cntr=0.3,0.1

Type RM Length L Ch R = 1 ,244     ,103.4,101.3,103.2
XS GIS Cut Line= 4
1659840.40943636488433.0551473821659452.97068446 488323.94883219
1659051.05864584488566.6547170041658987.59885027488944.073501187
#Sta/Elev= 30
       0 1070.28    39.6 1060.39    53.3  1059.1    70.3 1054.65    90.8 1044.82
   138.5 1030.65   145.3 1026.51   152.1 1019.32   155.5 1017.73   179.4 1017.78
     193 1009.81   216.9 1007.33   227.1 1002.52   233.9 1000.94   257.8  998.75
   318.8  999.35   434.9  997.82   477.4  995.12   630.7   994.1  644.65991.0183
   649.9  989.03   661.9  988.98   674.2991.0175   684.3  993.12   730.3  994.33
  1108.6  994.89  1141.6   997.2  1178.2 1003.75  1224.8    1009  1254.7  1014.1
#Mann= 9, -1 ,  0
       0     0.1       0      70    0.06       0  502.51     0.1       0
  644.65   0.045       0   674.2     0.1       0  722.51    0.05       0
  832.51     0.1       0  892.02    0.05       0 1202.02    0.06       0
Bank Sta=644.65,674.2
XS Rating Curve= 0 ,0
Exp/Cntr(USF)=0,0
Exp/Cntr=0.3,0.1

Type RM Length L Ch R = 1 ,143     ,107.6,107.6,107.6
XS GIS Cut Line= 4
1659805.89621421488360.1320489631659418.45746231488251.025733771
1659016.54542369488493.7316185851658953.08562812488871.150402768
#Sta/Elev= 30
       0 1061.74    34.4 1050.28    54.9 1048.26    68.5 1041.98    99.2 1033.78
   123.1  1021.4   147.5  1021.2     164 1012.97   170.8  1007.4   177.6 1004.85
   276.9  998.31   327.5  997.38   358.2 1001.27     378  999.92     404  995.55
   694.6  994.14  714.35990.7905   720.9  988.73   732.2  988.58  746.05990.7916
   778.2  997.41   806.9   994.5   872.9  993.62   889.5  993.57   909.5   998.6
   942.7  997.74   969.3  993.44  1161.8  994.03  1210.3  995.38  1254.7  999.39
#Mann= 6, -1 ,  0
       0     0.1       0      30    0.06       0  472.51     0.1       0
  714.35   0.045       0  746.05     0.1       0  962.02    0.05       0
Bank Sta=714.35,746.05
XS Rating Curve= 0 ,0
Exp/Cntr(USF)=0,0
Exp/Cntr=0.3,0.1
LCMann Table=0

Chan Stop Cuts=-1
Use User Specified Reach Order=0
Composite Channel Slope=5